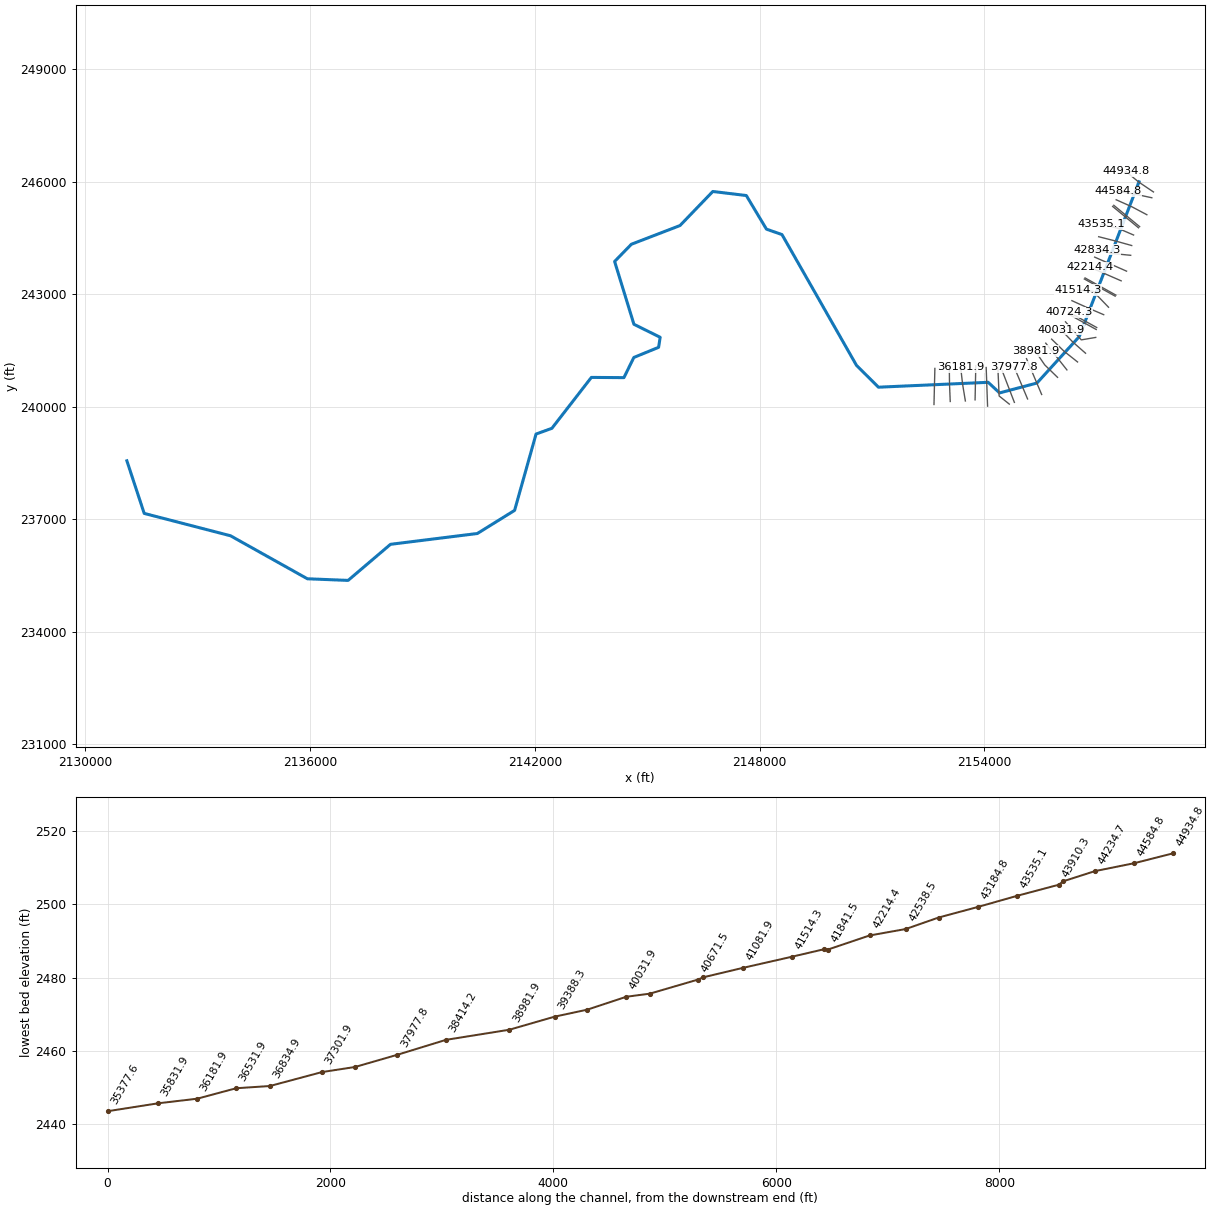
--- LAURELCK3.prj (project) ---

Proj Title=LAURELCK3
Current Plan=p01
Default Exp/Contr=0,0
English Units
Geom File=g01
Flow File=f01
Plan File=p01
BEGIN DESCRIPTION:
END DESCRIPTION:
DSS Export Rating Curves= 0
DSS Export Rating Curve Sorted= 0
DSS Export Volume Flow Curves= 0
DXF OffsetX= 0
DXF OffsetY= 0
DXF ScaleX= 0
DXF ScaleY= 0

--- LAURELCK3.p01 (plan) ---

Plan Title=Floodplain
Program Version=4.00
Geom File=g01
Flow File=f01
K Sum by GR=0
Std Step Tol=0.01
Critical Tol=0.01
Num of Std Step Trials=20
Max Error Tol=0.3
Flow Tol Ratio=0.001
Split Flow NTrial=30
Split Flow Tol=0.02
Split Flow Ratio=0.02
Log Output Level=0
Friction Slope Method=1
Unsteady Friction Slope Method=2
Unsteady Bridges Friction Slope Method=1
Global Log Level=0
CheckData=False
Run HTab=0
Run UNet=0
Run PostProcess=0
UNET Theta=0
UNET Theta Warmup=0
UNET ZTol=0
UNET ZSATol=0
UNET MxIter=0
UNET MaxInSteps=0
UNET DtIC=0
UNET DtMin=0
UNET MaxCRTS=0
UNET WFStab=0
UNET SFStab=0
UNET WFX=0
UNET SFX=0
UNET DSS MLevel=0
UNET DZMax Abort=0
UNET Convert EG Bridges=0
UNET Use Existing IB Tables=0
UNET Froude Limit=0
UNET Froude Power=0
Write IC File=0
Echo Input=False
Echo Output=False
Write Detailed=0

--- LAURELCK3.f01 (steady flow) ---

Flow Title=2010 USGS WV Regression Equation
Program Version=4.00
Number of Profiles=1
Profile Names=P100yr
River Rch & RM=LAURELCK3,Main      ,44934.8
532.7273
River Rch & RM=LAURELCK3,Main      ,43184.8
626.5578
River Rch & RM=LAURELCK3,Main      ,43184.8
573.6562
River Rch & RM=LAURELCK3,Main      ,42214.4
682.4513
River Rch & RM=LAURELCK3,Main      ,41081.9
757.2523
River Rch & RM=LAURELCK3,Main      ,38414.2
823.7810
River Rch & RM=LAURELCK3,Main      ,37977.8
 881.596
River Rch & RM=LAURELCK3,Main      ,37301.9
920.0235
River Rch & RM=LAURELCK3,Main      ,36834.9
1433.194
River Rch & RM=LAURELCK3,Main      ,34781.9
1512.581
River Rch & RM=LAURELCK3,Main      ,29528.2
1627.250
River Rch & RM=LAURELCK3,Main      ,29268.9
1950.540
River Rch & RM=LAURELCK3,Main      ,26368
2041.954
River Rch & RM=LAURELCK3,Main      ,22861.2
2268.736
River Rch & RM=LAURELCK3,Main      ,16214
2500.790
River Rch & RM=LAURELCK3,Main      ,11314.5
2669.500
River Rch & RM=LAURELCK3,Main      ,411.9
2962.349
River Rch & RM=LAURELCK3,Main      ,115
2963.980
Boundary for River Rch & Prof#=LAURELCK3,Main      ,1
Up Type=0
Dn Type=3
Dn Slope=0.010546

--- LAURELCK3.g01 (geometry) ---

Geom Title=LiDAR
Program Version=4.10

River Reach=LAURELCK3       ,Main
Reach XY= 30
     2158128.923      245996.101     2156534.305       241866.76
     2155404.965      240628.045     2154406.701      240364.156
     2154102.882      240647.142     2151174.468      240517.046
     2150587.604      241099.226     2148598.888      244587.941
     2148183.958      244732.906     2147646.631      245629.608
     2146751.666      245737.246     2145875.798      244828.392
     2144578.923      244330.129     2144131.007      243870.927
     2144645.763       242195.58     2145347.152      241848.358
     2145304.618      241580.128     2144644.028      241310.163
     2144379.271      240771.969     2143510.347      240778.045
     2142456.653      239420.564     2142033.784      239267.628
     2141460.868       237231.17     2140466.076      236613.983
     2138148.335      236325.913     2137016.391       235363.24
     2135929.585      235406.642     2133876.633      236554.212
     2131573.248      237150.566     2131110.756      238554.121

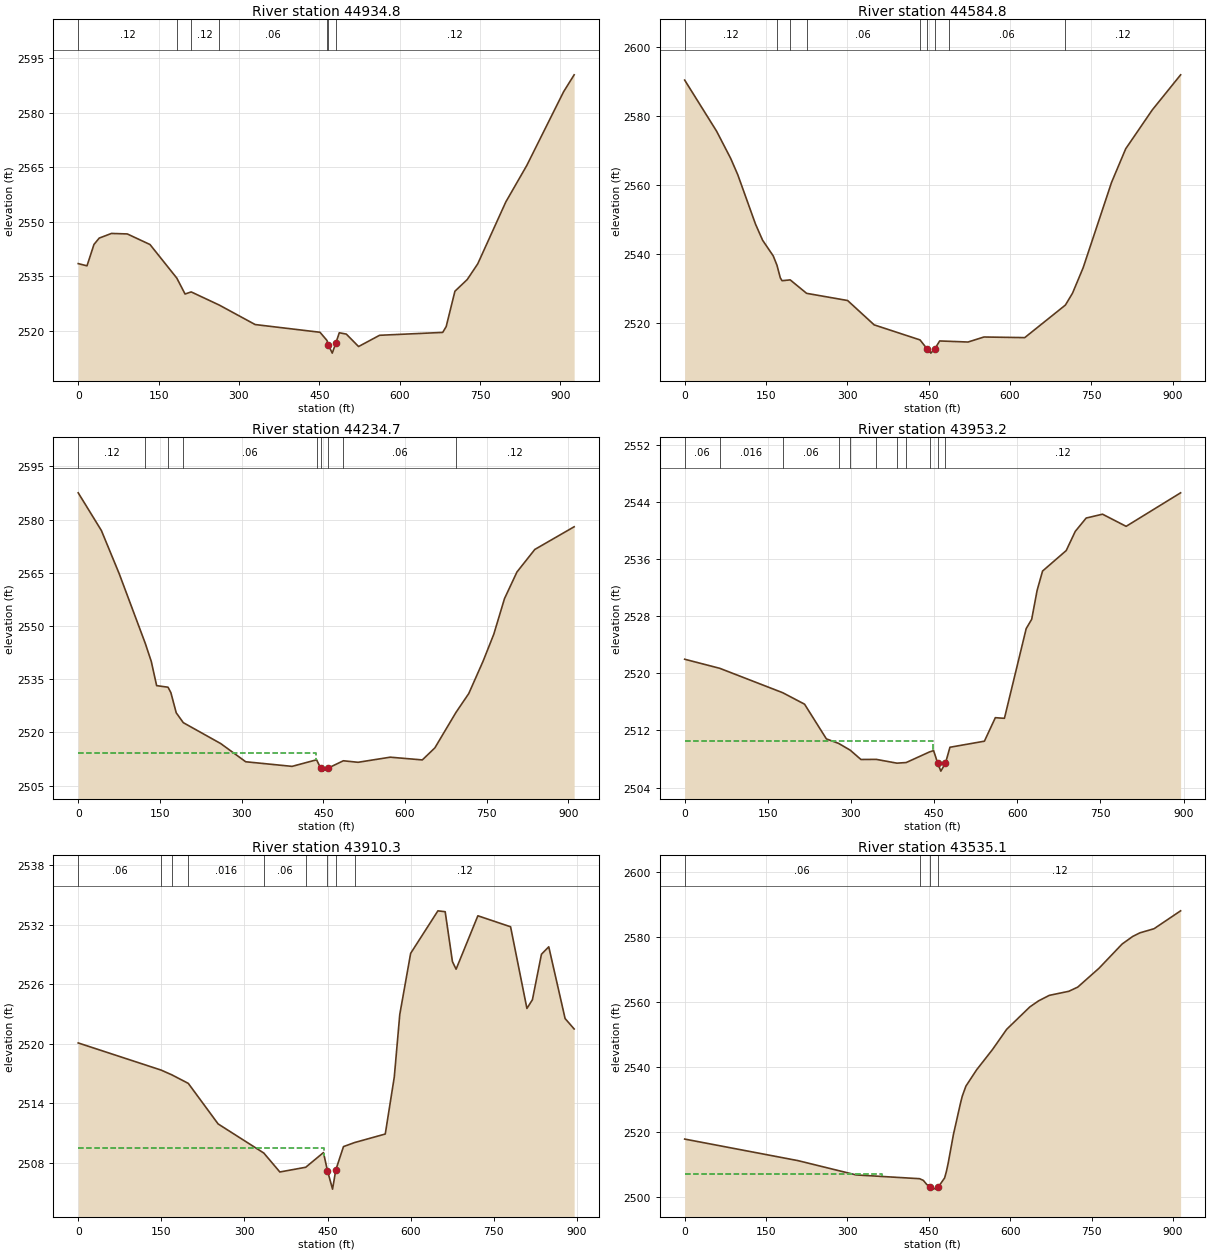
Type RM Length L Ch R = 1 ,44934.8 ,341.3,350,361.4
XS GIS Cut Line= 3
     2158514.913      245724.808     2158121.526      245989.398
     2157772.602      246275.753
#Sta/Elev= 30
       0  2538.5    16.4 2537.89    29.4 2543.76    39.2 2545.51    62.1 2546.79
    91.6 2546.65     134 2543.74  184.072534.503   199.4 2530.15  210.912530.721
  263.54 2527.09   330.2 2521.76   451.2 2519.64  464.242517.389   466.6  2516.2
   474.1 2513.91   480.6  2516.6   487.2  2519.5   500.3 2519.14   523.2 2515.72
   562.4 2518.81   680.2  2519.6   686.7  2521.2     703 2530.91     726 2534.13
   745.6 2538.44   797.9 2555.42   837.2 2565.49   905.8 2585.71   925.5 2590.36
#Mann= 7 ,-1 , 0
       0     .12       0  184.07    .016       0  210.91     .12       0
  263.54     .06       0  464.24     .12       0   466.6    .045       0
   480.6     .12       0
Bank Sta=466.6,480.6
XS Rating Curve= 0 ,0
Exp/Cntr=0.3,0.1

Type RM Length L Ch R = 1 ,44584.8 ,355.8,350.2,343.6
XS GIS Cut Line= 3
     2158471.169      245570.352     2158027.259      245665.474
     2157572.546      245739.756
#Sta/Elev= 30
       0 2590.45    58.8 2575.64    84.9 2567.71      98 2562.96   130.6 2548.67
   143.7 2543.98   163.3 2539.44   170.22536.736   176.4 2533.05   179.6 2532.23
  194.642532.465  224.842528.566   300.5 2526.48   349.5 2519.41  434.072515.045
   447.4 2512.39     454 2511.21   461.5 2512.48   470.3 2514.74  487.872514.641
   522.6 2514.43     552 2515.89   627.2 2515.71  702.21 2525.16   715.4 2528.63
     735 2536.02   787.3 2560.76   813.4 2570.51   862.4 2581.79   914.7 2591.98
#Mann= 9 ,-1 , 0
       0     .12       0   170.2    .016       0  194.64     .12       0
  224.84     .06       0  434.07     .12       0   447.4    .045       0
   461.5     .12       0  487.87     .06       0  702.21     .12       0
Bank Sta=447.4,461.5
XS Rating Curve= 0 ,0
Exp/Cntr=0.3,0.1

Type RM Length L Ch R = 1 ,44234.7 ,285.9,281.4,275.4
XS GIS Cut Line= 3
     2158338.079      245118.005     2157936.083      245330.825
     2157519.856      245516.646
#Sta/Elev= 30
       0 2587.52    42.5 2576.91    75.3 2564.71  123.222545.051   134.2 2539.97
     144 2533.17  164.982532.713   170.2 2531.17     180  2525.5  192.982522.723
   261.8 2516.82   307.6  2511.7   392.7  2510.4  437.742512.258     445 2509.96
   448.3 2509.06  458.172509.861  486.882511.979   513.9 2511.55   572.9 2512.99
   631.9 2512.22   654.9 2515.61  693.622525.595   717.2 2530.94   743.4 2540.03
   763.1 2547.64   782.8  2557.7   805.7 2565.21   838.5 2571.56   910.7 2577.95
#Mann= 9 ,-1 , 0
       0     .12       0  123.22    .016       0  164.98     .12       0
  192.98     .06       0  437.74     .12       0     445    .045       0
  458.17     .12       0  486.88     .06       0  693.62     .12       0
#XS Ineff= 2 , 0
          436.53 2514.19
Permanent Ineff=
       F       F
Bank Sta=445,458.17
XS Rating Curve= 0 ,0
Exp/Cntr=0.3,0.1

Type RM Length L Ch R = 1 ,43953.2 ,42.9,42.9,42.9
XS GIS Cut Line= 2
     2158146.054      244799.485      2157455.95      245369.146
#Sta/Elev= 30
       0 2521.97   63.392520.697  176.942517.283   216.3 2515.68   255.7 2510.82
  277.652510.195  298.582509.249     318 2507.94  345.912507.952  382.892507.426
  399.662507.511  441.84    2509   449.1 2509.18   456.7 2507.39   462.2 2506.31
  470.582507.432   478.6 2509.65   540.8  2510.5   560.5 2513.79   576.9  2513.7
   616.2 2526.26   626.1 2527.56   635.9 2531.61   645.7 2534.31   688.4 2537.18
   704.7 2539.86   724.4 2541.73   753.9 2542.27   796.5 2540.57   894.8 2545.26
#Mann= 11 ,-1 , 0
       0     .06       0   63.39    .016       0  176.94     .06       0
  277.65    .016       0  298.58     .12       0  345.91    .016       0
  382.89     .06       0  399.66    .016       0  441.84     .12       0
   456.7    .045       0  470.58     .12       0
#XS Ineff= 2 , 0
          448.92 2510.47
Permanent Ineff=
       F       F
Bank Sta=456.7,470.58
XS Rating Curve= 0 ,0
Exp/Cntr=0.3,0.1

Type RM Length L Ch R = 1 ,43910.3 ,367.1,375.2,384.8
XS GIS Cut Line= 2
     2158115.672      244769.103     2157425.568      245338.764
#Sta/Elev= 30
       0 2520.09  149.272517.357  168.742516.877  198.64 2516.01   252.4 2511.92
  334.842508.982   363.8 2507.07  410.522507.547   442.5 2509.03  449.622507.218
   458.9 2505.34  464.782507.279   478.6 2509.63  498.822510.042     554  2510.9
   570.3 2516.66   580.2 2522.97   599.8 2529.13     649 2533.42   662.1 2533.33
   675.2  2528.3   681.8 2527.53   721.1 2532.92   780.1 2531.81   809.6 2523.57
   819.5 2524.45   835.8 2529.04     849 2529.79   878.5 2522.55   894.8  2521.5
#Mann= 9 ,-1 , 0
       0     .06       0  149.27    .016       0  168.74     .12       0
  198.64    .016       0  334.84     .06       0  410.52    .016       0
  449.62    .045       0  464.78    .016       0  498.82     .12       0
#XS Ineff= 2 , 0
          443.76 2509.51
Permanent Ineff=
       F       F
Bank Sta=449.62,464.78
XS Rating Curve= 0 ,0
Exp/Cntr=0.3,0.1

Type RM Length L Ch R = 1 ,43535.1 ,347.2,350.3,349.2
XS GIS Cut Line= 3
     2157984.342      244576.377      2157565.31      244756.775
     2157120.685      244866.793
#Sta/Elev= 30
       0 2517.74   208.6  2511.1   316.1 2506.68  433.012505.516   439.9    2505
   446.4 2503.71     453 2503.01   462.8  2502.3  467.712503.011   479.1 2505.74
   482.4  2507.7   485.7 2510.27   495.5 2519.23   508.6 2528.93   511.8 2531.02
   518.4 2534.07     538 2539.07   567.4 2545.36   593.6 2551.61   636.2  2558.5
   652.5 2560.39   672.1 2562.07   708.1 2563.33   724.5 2564.61   763.8 2570.44
   806.3  2577.9   825.9 2580.25     839 2581.35   865.2 2582.63   914.2 2588.15
#Mann= 4 ,-1 , 0
       0     .06       0  433.01     .12       0     453    .045       0
  467.71     .12       0
#XS Ineff= 2 , 0
           362.9 2506.91
Permanent Ineff=
       F       F
Bank Sta=453,467.71
XS Rating Curve= 0 ,0
Exp/Cntr=0.3,0.1

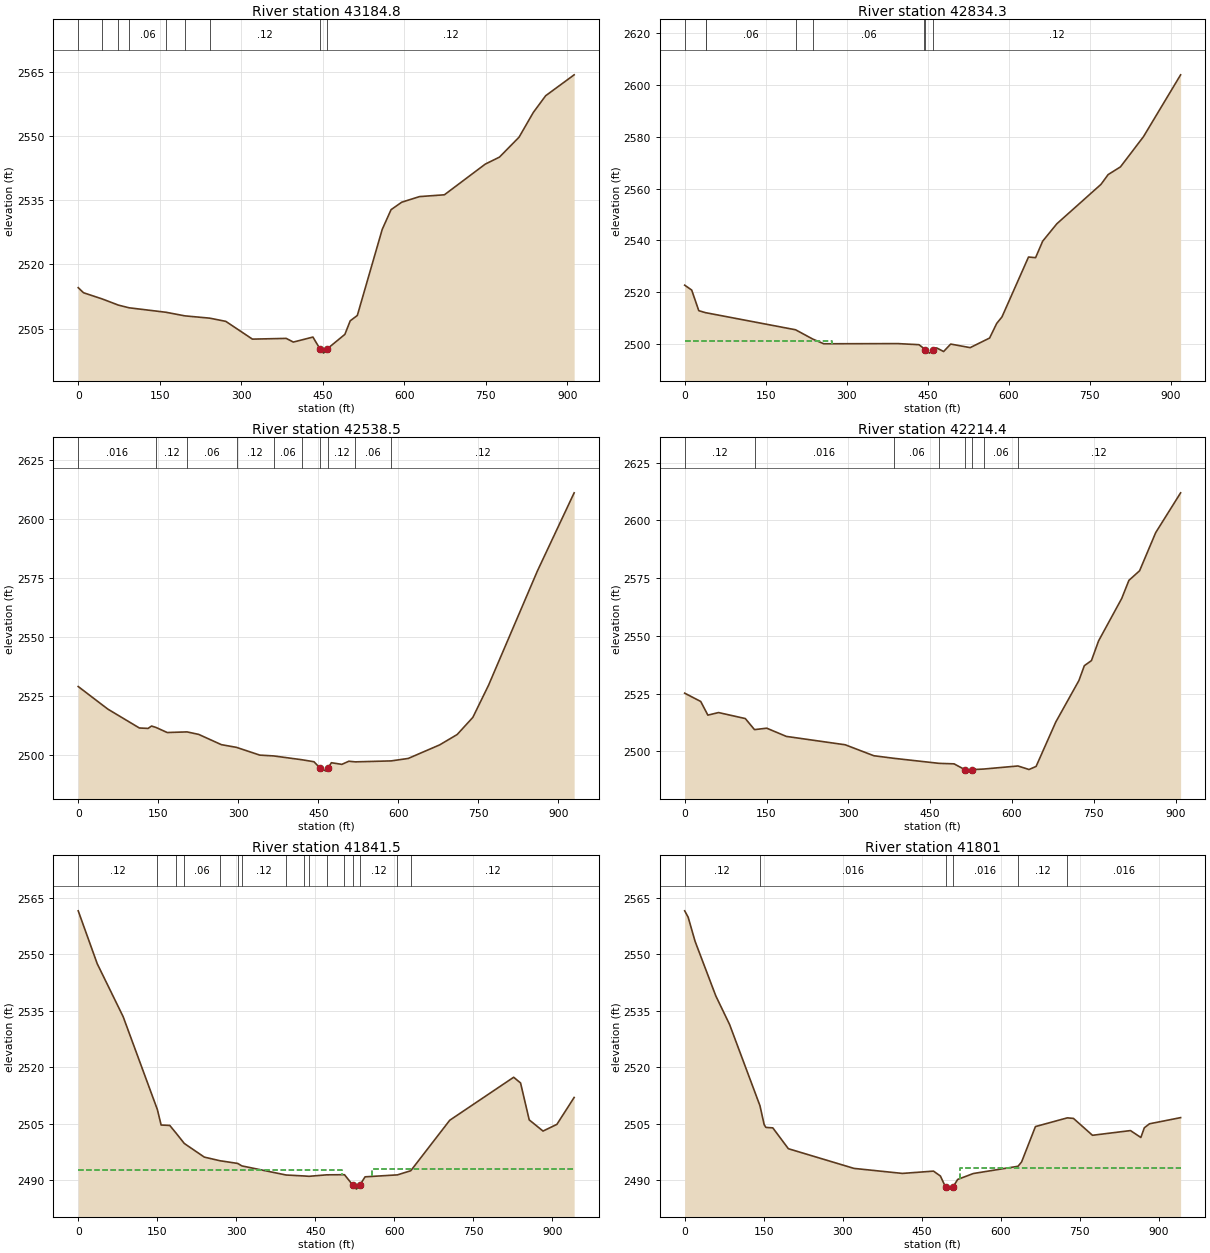
Type RM Length L Ch R = 1 ,43184.8 ,345.3,350.5,350.8
XS GIS Cut Line= 3
     2157934.459      244295.883     2157496.488      244417.875
     2157052.929      244530.857
#Sta/Elev= 30
       0 2514.56     9.8 2513.37   44.582511.905      742510.481   93.662509.856
  161.562508.812  195.992507.977  241.842507.439   271.5 2506.69   320.5 2502.54
   382.7 2502.71   395.8 2501.85   431.8 2503.02   444.8 2500.26   451.4 2499.27
  458.612500.314   490.6 2503.65   500.4 2506.81   513.5 2508.07   559.3 2528.17
   575.6 2532.78   595.2 2534.52   627.9 2535.83   673.7 2536.25   748.9 2543.42
     775 2545.05     811  2549.7   837.2 2555.47     860 2559.39   912.4 2564.27
#Mann= 9 ,-1 , 0
       0     .12       0   44.58     .06       0      74     .12       0
   93.66     .06       0  161.56     .12       0  195.99     .06       0
  241.84     .12       0   444.8    .045       0  458.61     .12       0
Bank Sta=444.8,458.61
XS Rating Curve= 0 ,0
Exp/Cntr=0.3,0.1

Type RM Length L Ch R = 1 ,42834.3 ,302.6,295.8,291
XS GIS Cut Line= 3
     2157907.092      244035.199      2157456.22      244079.606
     2157002.323      244179.214
#Sta/Elev= 30
       0 2522.66      13 2520.76    26.1  2512.8   39.562511.972   39.822511.985
  205.222505.423  237.072501.829   257.5 2500.01   394.4 2500.08   433.5 2499.66
  443.242498.144   445.6 2497.59     453  2496.4   459.6  2497.7   466.1 2498.43
   479.2 2497.02   492.3  2499.9   528.3 2498.52   564.3 2502.23   577.4 2507.86
   587.2 2510.39   636.3 2533.53   649.4 2533.29   662.5 2539.65   688.7 2546.37
   770.5 2561.62   783.6 2565.37   806.5 2568.37     849 2580.02   917.8 2603.93
#Mann= 8 ,-1 , 0
       0    .016       0   39.56     .12       0   39.82     .06       0
  205.22     .12       0  237.07     .06       0  443.24     .12       0
   445.6    .045       0   459.6     .12       0
#XS Ineff= 2 , 0
          273.26 2500.99
Permanent Ineff=
       F       F
Bank Sta=445.6,459.6
XS Rating Curve= 0 ,0
Exp/Cntr=0.3,0.1

Type RM Length L Ch R = 1 ,42538.5 ,323.6,324.1,324
XS GIS Cut Line= 2
     2157796.862      243612.273     2156945.892       243986.35
#Sta/Elev= 30
       0 2529.13    55.6 2519.54   114.6 2511.55   130.9 2511.36   137.5 2512.38
  145.862511.765   166.9 2509.62  203.982509.887   225.8 2508.83   268.4 2504.47
  296.772503.325   340.4 2500.04  366.712499.688  418.86 2498.09   441.9 2497.23
   453.42494.527   464.8 2493.25     468 2494.56   474.6 2496.81   494.2 2496.12
   507.3 2497.45  519.352497.179  586.782497.589   618.6 2498.63   677.5 2504.38
   710.3 2508.77   739.7 2516.04   769.2  2529.7   860.8 2578.18   929.6 2611.28
#Mann= 10 ,-1 , 0
       0    .016       0  145.86     .12       0  203.98     .06       0
  296.77     .12       0  366.71     .06       0  418.86     .12       0
   453.4    .045       0     468     .12       0  519.35     .06       0
  586.78     .12       0
Bank Sta=453.4,468
XS Rating Curve= 0 ,0
Exp/Cntr=0.3,0.1

Type RM Length L Ch R = 1 ,42214.4 ,373.7,372.8,369.9
XS GIS Cut Line= 2
     2157652.482      243354.138     2156819.012      243717.277
#Sta/Elev= 30
       0 2525.22    29.4 2521.63    42.5 2515.72    62.1 2516.83   111.2 2514.23
  127.992509.444   150.4 2510.07   186.4 2506.51   294.3 2502.89   346.6 2498.16
  383.352497.042  466.272494.855   493.8 2494.64   513.4 2492.16     520 2491.49
   526.5 2492.13  547.962492.389  610.892493.719   631.2 2492.19   644.2 2493.53
   680.2  2512.7   722.7  2530.7   732.6 2537.11   745.6  2539.3   758.7 2547.83
   801.2 2566.23   814.3 2574.02   833.9 2578.18   863.4 2594.67   909.1  2611.9
#Mann= 8 ,-1 , 0
       0     .12       0  127.99    .016       0  383.35     .06       0
  466.27     .12       0   513.4    .045       0   526.5     .12       0
  547.96     .06       0  610.89     .12       0
Bank Sta=513.4,526.5
XS Rating Curve= 0 ,0
Exp/Cntr=0.3,0.1

Type RM Length L Ch R = 1 ,41841.5 ,41.8,40.6,40.1
XS GIS Cut Line= 2
     2157511.867      242973.573     2156689.384      243431.472
#Sta/Elev= 30
       0 2561.47    36.1 2547.44    85.3  2533.4  150.252508.774   157.4 2504.66
   173.8 2504.55  186.322502.423  201.432499.765   239.4 2496.15  269.05 2495.19
  302.852494.472  310.542493.823  394.512491.406  429.182491.146  438.082491.056
  471.892491.451  505.432491.485   521.5  2488.7   528.1 2487.66   534.6 2488.73
   544.5 2490.92  605.91 2491.44  631.272492.538   705.2 2505.92   826.6 2517.33
   839.7 2515.81   856.1 2506.03   882.3 2503.06   908.6 2504.83   941.4 2511.97
#Mann= 16 ,-1 , 0
       0     .12       0  150.25    .016       0  186.32     .12       0
  201.43     .06       0  269.05     .12       0  302.85    .016       0
  310.54     .12       0  394.51    .016       0  429.18     .06       0
  438.08     .12       0  471.89    .016       0  505.43     .12       0
   521.5    .045       0   534.6     .12       0  605.91     .06       0
  631.27     .12       0
#XS Ineff= 2 , 0
           499.8 2492.64  558.06         2492.87
Permanent Ineff=
       F       F
Bank Sta=521.5,534.6
XS Rating Curve= 0 ,0
Exp/Cntr=0.3,0.1

Type RM Length L Ch R = 1 ,41801   ,290.1,286.7,280.5
XS GIS Cut Line= 2
     2157492.336      242945.361     2156669.853      243403.261
#Sta/Elev= 30
       0 2561.57     6.6 2559.88    19.7 2553.49      59 2539.02    85.3 2531.38
  142.93 2509.83   150.9 2504.81   154.2 2504.08   167.3 2503.96   196.8 2498.43
   321.4  2493.2   413.3 2491.87   472.3 2492.48   485.4 2491.18   495.3 2488.22
   498.6  2487.7  508.982488.194   518.2 2490.27   547.8 2491.84  632.792493.765
   639.6 2494.93   665.8  2504.3  726.332506.619     738 2506.47   774.1 2501.99
   846.2 2503.24   865.9 2501.41   872.5 2503.98   882.3 2505.04   941.4 2506.68
#Mann= 6 ,-1 , 0
       0     .12       0  142.93    .016       0   495.3    .045       0
  508.98    .016       0  632.79     .12       0  726.33    .016       0
#XS Ineff= 2 , 0
                          522.07         2493.39
Permanent Ineff=
       F       F
Bank Sta=495.3,508.98
XS Rating Curve= 0 ,0
Exp/Cntr=0.3,0.1

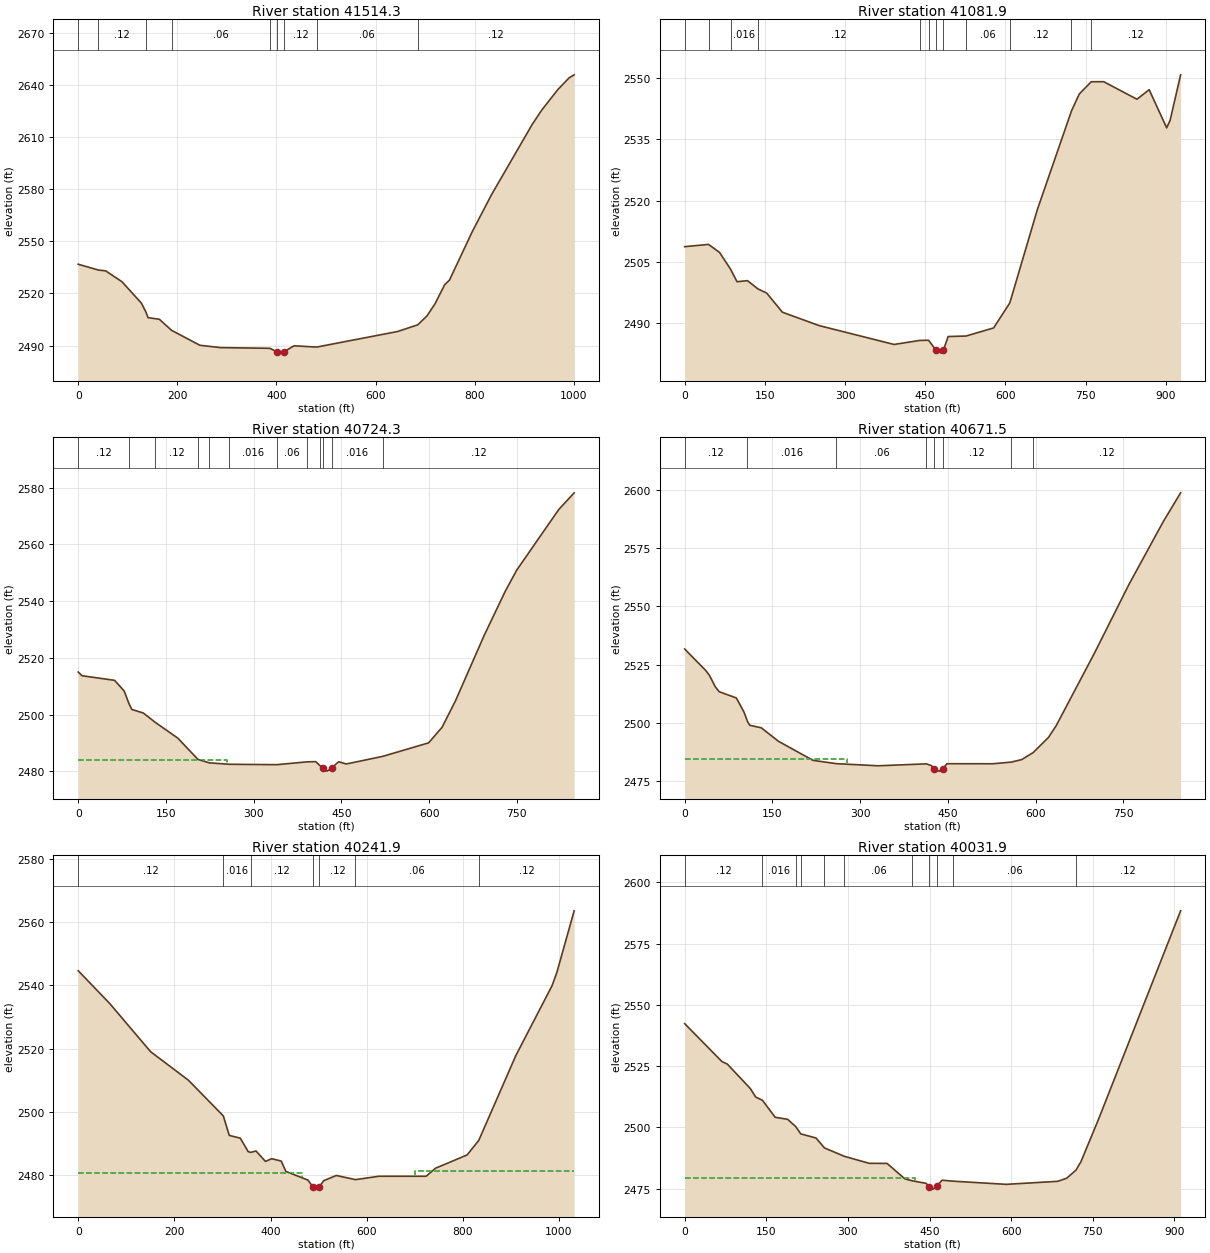
Type RM Length L Ch R = 1 ,41514.3 ,421.5,432.4,439.2
XS GIS Cut Line= 3
     2157315.594      242649.736     2156904.328      243076.315
     2156497.437      243109.129
#Sta/Elev= 30
       0 2536.84   40.772533.484    55.6 2532.99    88.4 2526.74   127.7 2514.36
  136.752509.221   140.8 2506.08   163.7 2505.15  188.352498.795   245.5 2490.18
   288.1 2488.82  386.632488.434  400.872486.485   409.2 2485.66   415.8 2486.49
   435.4 2489.88  481.142489.139   644.8 2498.12  685.162501.948   703.6 2507.01
   719.9 2513.99   739.5 2525.02   749.3 2527.75     795 2555.48   834.2 2576.94
   915.8 2617.13   935.4 2625.56   968.1 2637.44     991 2644.21  1000.8 2645.85
#Mann= 9 ,-1 , 0
       0     .06       0   40.77     .12       0  136.75    .016       0
  188.35     .06       0  386.63     .12       0  400.87    .045       0
   415.8     .12       0  481.14     .06       0  685.16     .12       0
Bank Sta=400.87,415.8
XS Rating Curve= 0 ,0
Exp/Cntr=0.3,0.1

Type RM Length L Ch R = 1 ,41081.9 ,358.9,357.6,354.3
XS GIS Cut Line= 3
     2157186.665      242451.001     2156748.578      242638.508
     2156337.818      242825.212
#Sta/Elev= 30
       0 2508.71   44.66 2509.26    65.3  2507.3   85.722503.225    97.9 2500.14
   117.5 2500.39     1372498.386   153.4 2497.36   182.8 2492.68   251.3 2489.41
   391.7 2484.79  439.362485.769  456.152485.823     470 2483.43   479.8 2482.67
     484  2483.4   492.9 2486.73  526.122486.848   577.9 2488.83  608.192494.955
   659.6 2517.73  723.512541.899   738.1 2546.05  760.512549.049   783.9 2549.06
     846 2544.77   868.9  2547.1   901.6 2537.77   908.1 2539.63   927.7 2550.74
#Mann= 12 ,-1 , 0
       0     .08       0   44.66     .06       0   85.72    .016       0
     137     .12       0  439.36     .06       0  456.15     .12       0
     470    .045       0     484     .12       0  526.12     .06       0
  608.19     .12       0  723.51     .06       0  760.51     .12       0
Bank Sta=470,484
XS Rating Curve= 0 ,0
Exp/Cntr=0.3,0.1

Type RM Length L Ch R = 1 ,40724.3 ,52.7,52.8,52.6
XS GIS Cut Line= 2
     2157000.655      242108.512     2156258.467      242518.669
#Sta/Elev= 30
       0    2515     6.6  2513.7    62.2 2512.08    78.6 2508.31   86.882503.824
    91.7 2501.82   111.3 2500.56  131.332497.332   170.2 2491.73  204.832484.202
  224.382482.991  258.122482.497  339.522482.356  391.982483.358     406 2483.42
  413.652481.974   419.1 2481.21   425.6 2480.08  433.522481.242   445.3 2483.38
   458.4 2482.59  520.992485.298   599.2 2490.05   622.1 2495.52     645 2504.82
   694.1 2527.89   730.1 2543.42   749.8 2550.92   821.8 2572.31     848 2578.16
#Mann= 12 ,-1 , 0
       0     .12       0   86.88    .016       0  131.33     .12       0
  204.83     .06       0  224.38     .12       0  258.12    .016       0
  339.52     .06       0  391.98     .12       0  413.65    .016       0
   419.1    .045       0  433.52    .016       0  520.99     .12       0
#XS Ineff= 2 , 0
          254.72 2483.97
Permanent Ineff=
       F       F
Bank Sta=419.1,433.52
XS Rating Curve= 0 ,0
Exp/Cntr=0.3,0.1

Type RM Length L Ch R = 1 ,40671.5 ,436.1,429.6,420.3
XS GIS Cut Line= 2
     2156986.549      242056.429     2156244.361      242466.585
#Sta/Elev= 30
       0 2531.74      36 2522.56    42.6 2520.34    52.4 2515.53    58.9 2513.46
    88.4 2510.76   101.5 2504.67  107.412500.708   111.3 2499.06     131 2497.98
   160.4 2492.19   219.4 2484.03  259.262482.614   330.7  2481.7  413.362482.525
   422.4  2481.7   425.6  2480.5   435.4 2479.41  441.092480.437   448.6 2482.58
   527.1 2482.57  558.312483.277   576.2 2484.35   595.9 2487.36   622.1 2493.87
   635.2 2498.87   700.6 2529.94   759.6 2559.39   818.5 2586.41     848 2598.68
#Mann= 8 ,-1 , 0
       0     .12       0  107.41    .016       0  259.26     .06       0
  413.36     .12       0   425.6    .045       0  441.09     .12       0
  558.31     .06       0   595.9     .12       0
#XS Ineff= 2 , 0
          277.33 2484.57
Permanent Ineff=
       F       F
Bank Sta=425.6,441.09
XS Rating Curve= 0 ,0
Exp/Cntr=0.3,0.1

Type RM Length L Ch R = 1 ,40241.9 ,206.7,210,210.3
XS GIS Cut Line= 3
     2156974.331      241844.705     2156587.128      241779.078
     2156167.112      242260.346
#Sta/Elev= 30
       0 2544.67    65.4 2534.32   150.5 2519.07   229.1 2510.05   301.82498.753
   314.2 2492.58   337.1 2491.71   353.4 2487.48   358.72487.202   369.8 2487.66
   389.4 2484.35   402.6 2485.22   422.2 2484.46     432 2481.19   477.9 2478.44
   487.8 2476.38   494.3 2475.59  501.652476.387   510.6 2478.26   536.9 2479.91
  576.712478.592   625.3 2479.66   723.6 2479.66   743.2  2482.2   808.8 2486.39
  833.082490.988   910.3 2517.86   985.6 2539.94   995.5  2544.1  1031.5 2563.61
#Mann= 7 ,-1 , 0
       0     .12       0   301.8    .016       0   358.7     .12       0
   487.8    .045       0  501.65     .12       0  576.71     .06       0
  833.08     .12       0
#XS Ineff= 2 , 0
          464.99 2480.73  700.03         2481.24
Permanent Ineff=
       F       F
Bank Sta=487.8,501.65
XS Rating Curve= 0 ,0
Exp/Cntr=0.3,0.1

Type RM Length L Ch R = 1 ,40031.9 ,347.9,350,349.8
XS GIS Cut Line= 3
     2156701.894      241423.089     2156358.856       241724.69
     2156043.033      242051.794
#Sta/Elev= 30
       0 2542.33    68.5 2526.84    78.3 2525.83   120.7 2515.82   130.5 2512.36
  142.932511.026   166.4 2504.09   189.2 2503.26  203.942500.333   213.42497.306
   241.4 2495.63  256.912491.576   293.42488.154   339.3 2485.28   371.9 2485.26
   404.6 2478.97  418.392478.136   443.7 2477.12   449.3 2475.77   456.8 2474.75
   463.3 2475.98   473.1 2478.39  493.95 2477.99   590.9  2476.7   685.8 2477.94
   702.1  2479.2  718.992482.466   728.3 2485.94     761 2503.48   911.5  2588.4
#Mann= 11 ,-1 , 0
       0     .12       0  142.93    .016       0  203.94     .06       0
   213.4    .016       0  256.91     .12       0   293.4     .06       0
  418.39     .12       0   449.3    .045       0   463.3     .12       0
  493.95     .06       0  718.99     .12       0
#XS Ineff= 2 , 0
          423.68 2479.45
Permanent Ineff=
       F       F
Bank Sta=449.3,463.3
XS Rating Curve= 0 ,0
Exp/Cntr=0.3,0.1

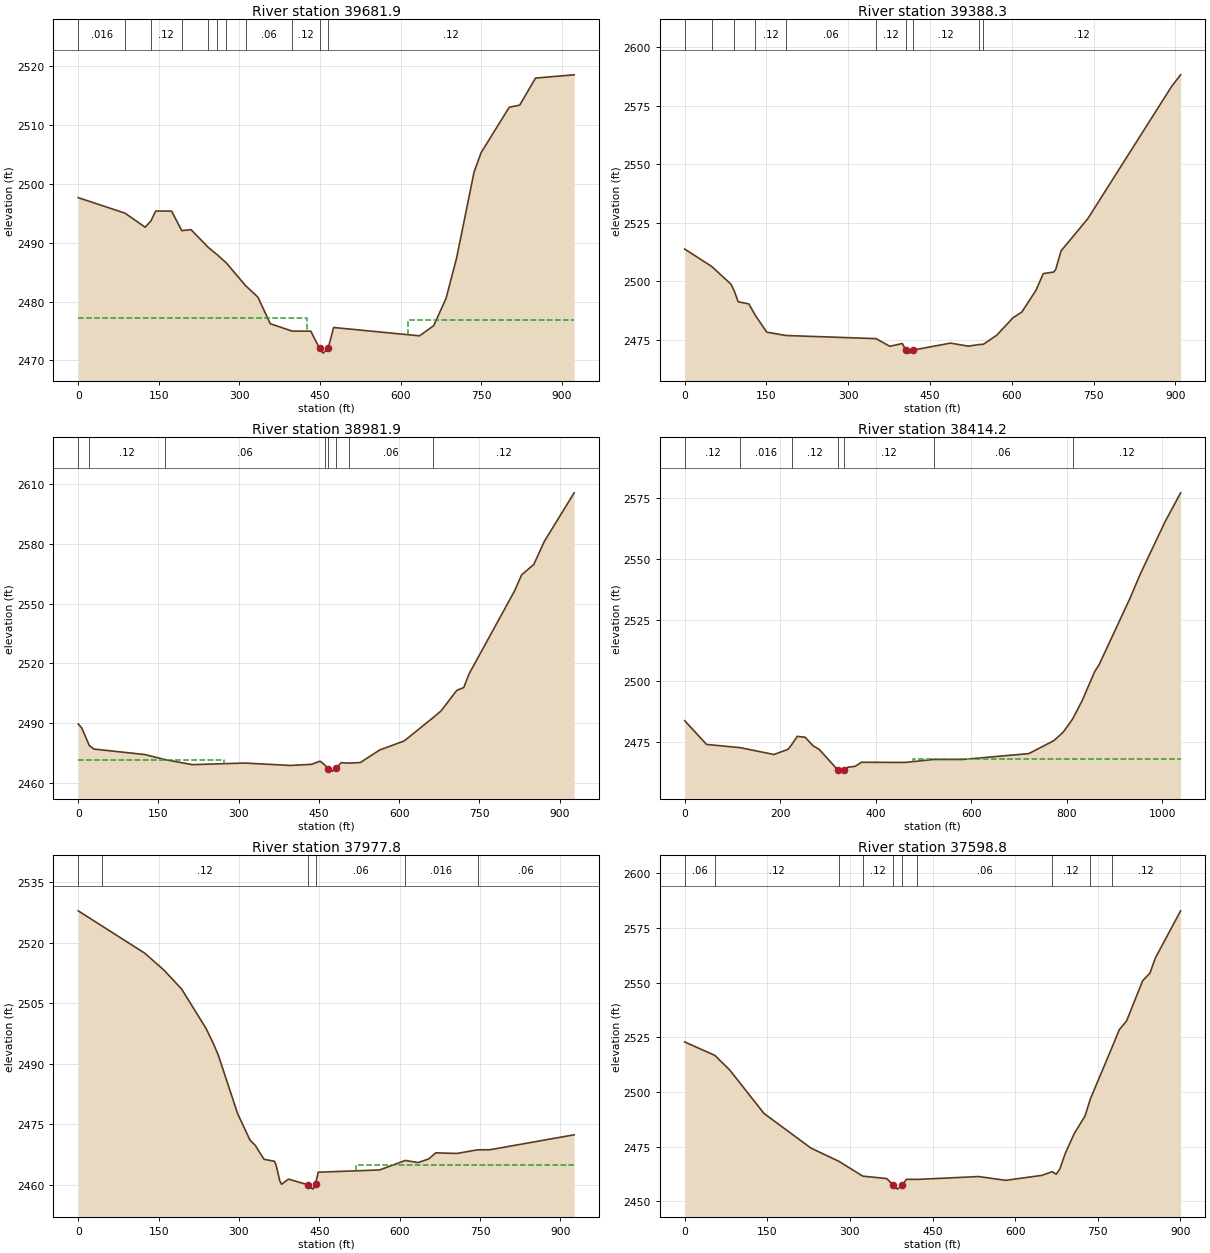
Type RM Length L Ch R = 1 ,39681.9 ,293.9,293.6,287.7
XS GIS Cut Line= 3
      2156488.73      241189.853     2156129.049      241475.273
     2155796.493      241798.918
#Sta/Elev= 30
       0 2497.68   87.272495.031   124.6 2492.65  135.262493.707   144.3  2495.4
   173.8 2495.39  192.772492.066   209.9 2492.24  242.432489.191  259.192487.933
  275.822486.565  311.43 2482.72   334.5 2480.75   357.5 2476.24  398.092474.978
   432.9 2474.97   449.3 2472.03   455.9 2471.23  465.212472.049   475.5 2475.59
   635.6 2474.17   661.8 2475.91   684.7 2480.53   704.3 2487.38   736.9 2502.04
     750 2505.33   802.3 2513.05   821.9 2513.42   851.3 2518.02   923.2 2518.57
#Mann= 11 ,-1 , 0
       0    .016       0   87.27     .04       0  135.26     .12       0
  192.77    .016       0  242.43     .12       0  259.19     .06       0
  275.82     .12       0  311.43     .06       0  398.09     .12       0
   449.3    .045       0  465.21     .12       0
#XS Ineff= 2 , 0
          426.21 2477.26  614.04         2476.93
Permanent Ineff=
       F       F
Bank Sta=449.3,465.21
XS Rating Curve= 0 ,0
Exp/Cntr=0.3,0.1

Type RM Length L Ch R = 1 ,39388.3 ,401.1,406.4,403.7
XS GIS Cut Line= 2
     2156204.301      240978.422     2155639.905      241691.575
#Sta/Elev= 30
       0 2513.79   49.532506.356    85.1 2498.74   91.082495.813    98.1 2491.25
   117.8 2490.34  128.652485.777   150.5 2478.27  185.722476.848  351.032475.501
   376.2 2472.23   399.1 2473.42   405.7 2470.65   412.2 2469.31  419.472470.628
   487.4 2473.59   520.2 2472.29  538.852472.941   547.92473.108   572.5 2477.01
     602  2484.4   618.3 2486.86   644.5 2496.27   657.6 2503.29   677.2 2503.99
   680.5 2505.16   690.3    2513   739.4 2526.81   893.1 2583.32   909.5 2588.24
#Mann= 10 ,-1 , 0
       0    .016       0   49.53     .12       0   91.08    .016       0
  128.65     .12       0  185.72     .06       0  351.03     .12       0
   405.7    .045       0  419.47     .12       0  538.85     .06       0
   547.9     .12       0
Bank Sta=405.7,419.47
XS Rating Curve= 0 ,0
Exp/Cntr=0.3,0.1

Type RM Length L Ch R = 1 ,38981.9 ,577,567.7,560.5
XS GIS Cut Line= 3
     2155954.691      240779.544     2155613.534      241110.339
     2155357.912      241483.381
#Sta/Elev= 30
       0 2489.47     6.6 2487.48   20.72 2478.62    29.5 2476.84   124.5 2474.08
  162.442471.521     213    2469   311.3  2469.8   396.5  2468.6   435.9 2469.14
   452.3 2470.75  460.942468.912   467.7 2466.96   475.2 2465.74   482.7 2467.21
   491.6 2469.99  505.842469.759   527.6 2470.06   563.7 2476.37   609.6 2480.92
  663.092492.528   678.4 2495.98   707.9 2506.35     721  2507.8   730.8  2514.6
     816 2556.39   829.1 2564.42     852 2569.72   871.7 2581.31   927.4 2605.72
#Mann= 8 ,-1 , 0
       0    .016       0   20.72     .12       0  162.44     .06       0
  460.94     .12       0   467.7    .045       0   482.7     .12       0
  505.84     .06       0  663.09     .12       0
#XS Ineff= 2 , 0
          272.57 2471.39
Permanent Ineff=
       F       F
Bank Sta=467.7,482.7
XS Rating Curve= 0 ,0
Exp/Cntr=0.3,0.1

Type RM Length L Ch R = 1 ,38414.2 ,435.6,436.5,436.1
XS GIS Cut Line= 2
     2155530.525      240322.147     2155125.822      241278.121
#Sta/Elev= 30
       0 2483.65    45.8 2473.91  116.17  2472.6   186.7 2469.79   216.1 2471.88
  223.942473.799   235.8 2477.23   252.2 2476.85   268.5  2473.4   281.6 2471.88
   320.9  2463.4   327.5 2462.98     334 2463.31   340.6 2464.55     357 2464.96
     370 2466.61   461.8 2466.54  521.152467.766   582.9 2467.76   720.4 2470.16
   772.8 2475.47   792.5 2478.98     8122484.314   831.8 2491.77     858 2503.66
   867.8 2506.71   933.3 2534.28     953 2543.44  1005.4 2565.09  1038.1 2576.98
#Mann= 7 ,-1 , 0
       0     .12       0  116.17    .016       0  223.94     .12       0
   320.9    .045       0     334     .12       0  521.15     .06       0
     812     .12       0
#XS Ineff= 2 , 0
                          478.19         2468.09
Permanent Ineff=
       F       F
Bank Sta=320.9,334
XS Rating Curve= 0 ,0
Exp/Cntr=0.3,0.1

Type RM Length L Ch R = 1 ,37977.8 ,378.1,379,377
XS GIS Cut Line= 2
     2155154.261      240204.017     2154795.497      241057.175
#Sta/Elev= 30
       0 2527.95   44.22 2524.21   124.3 2517.43   160.2 2513.22     193 2508.54
   238.7 2498.74   251.8 2495.13   261.6 2492.09   297.6 2477.59   320.5 2471.09
   330.3 2469.78   346.7 2466.31   366.3  2465.8   369.6 2464.76   376.1 2460.98
   379.4  2460.1   392.4 2461.38   427.9    2460   438.2  2458.9   442.9 2460.27
     448  2463.1   562.5 2463.66  610.482466.017   634.5 2465.49   654.1  2466.4
   667.2  2467.9   706.4 2467.75  745.222468.645   768.5 2468.68   925.5 2472.38
#Mann= 6 ,-1 , 0
       0     .06       0   44.22     .12       0   427.9    .045       0
   442.9     .06       0  610.48    .016       0  745.22     .06       0
#XS Ineff= 2 , 0
                          519.31         2464.81
Permanent Ineff=
       F       F
Bank Sta=427.9,442.9
XS Rating Curve= 0 ,0
Exp/Cntr=0.3,0.1

Type RM Length L Ch R = 1 ,37598.8 ,303.6,296.8,289
XS GIS Cut Line= 2
      2154802.06      240112.139     2154478.297      240952.171
#Sta/Elev= 30
       0  2522.9   54.582516.776    81.8 2510.07     144 2490.18   229.2 2474.35
  280.152468.262  323.412461.503   366.6 2460.41  378.862457.407   386.3 2455.57
  394.682457.426   402.7 2460.08  422.29 2460.02   533.6 2461.32   582.7  2459.6
   648.2 2461.85  667.362463.572   674.4 2462.38   680.9 2464.73   690.8 2471.83
   707.1 2480.95   726.8 2489.01  736.352496.763  775.592520.301     789  2528.5
     802 2532.41   831.5 2550.95   844.6  2554.4   854.4 2561.28   900.3 2582.87
#Mann= 10 ,-1 , 0
       0     .06       0   54.58     .12       0  280.15     .06       0
  323.41     .12       0  378.86    .045       0  394.68     .12       0
  422.29     .06       0  667.36     .12       0  736.35    .016       0
  775.59     .12       0
Bank Sta=378.86,394.68
XS Rating Curve= 0 ,0
Exp/Cntr=0.3,0.1

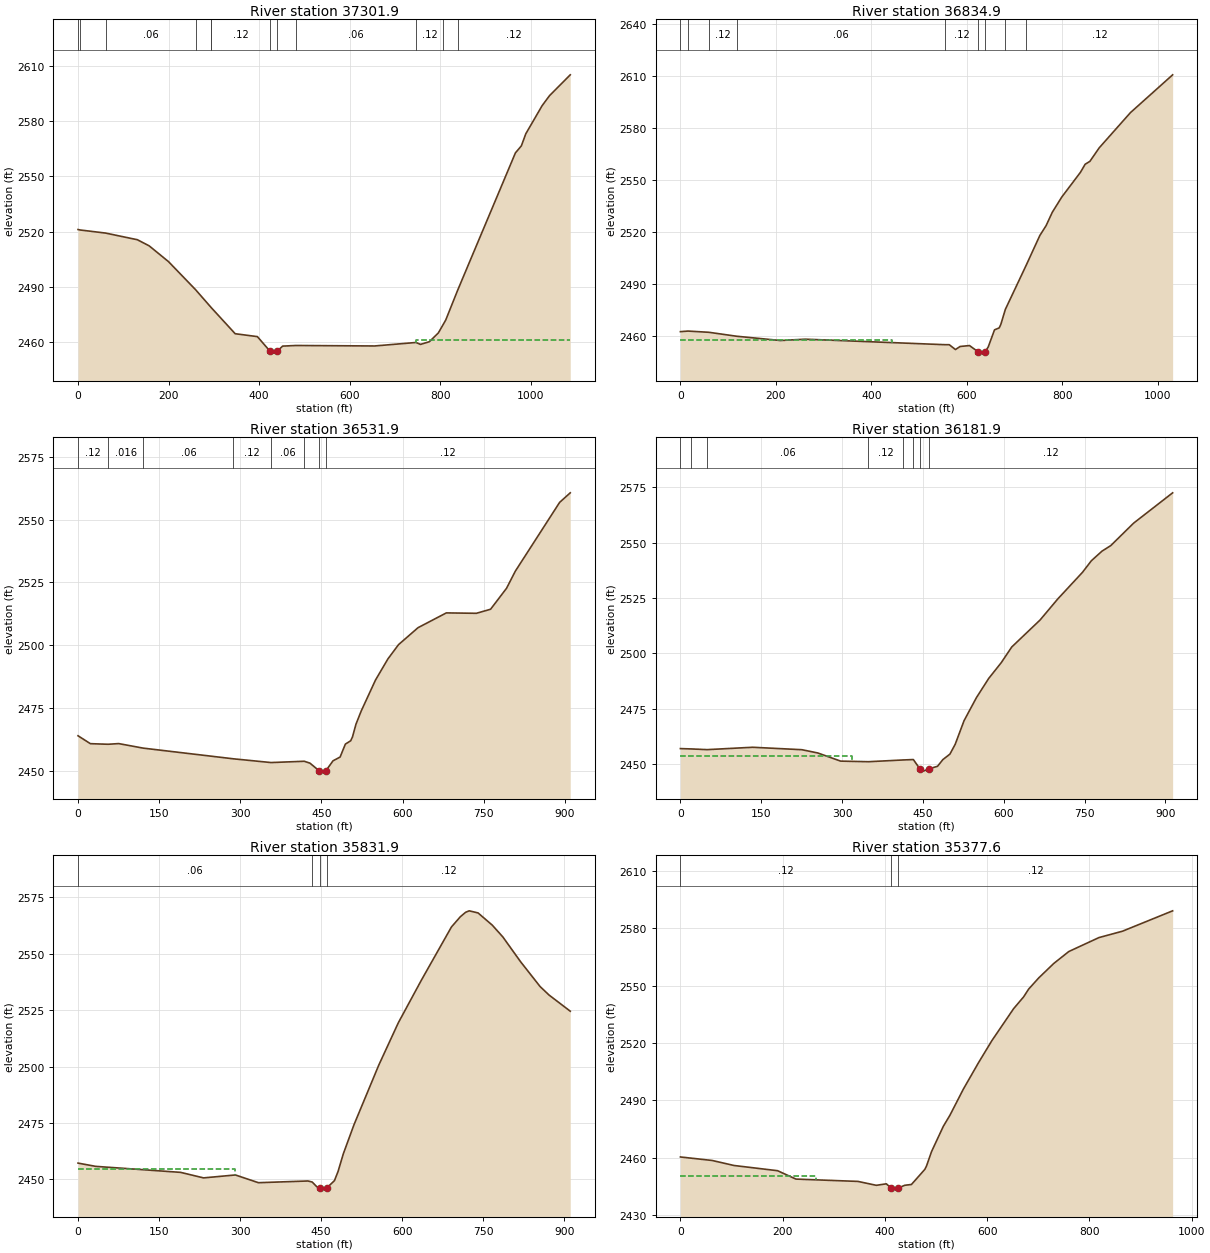
Type RM Length L Ch R = 1 ,37301.9 ,466,467,466.4
XS GIS Cut Line= 3
      2154666.43        240066.2     2154395.169       240282.77
     2154362.356      241022.174
#Sta/Elev= 30
       0 2521.16    5.14  2520.9   60.88 2519.24     131 2515.64   157.2 2512.31
   199.8 2503.78  259.722488.533  293.072479.174  294.34 2478.82   347.1  2464.7
   396.2 2463.12   424.22455.176     429 2454.18  440.052455.229   451.9 2457.98
  481.29 2458.32     655 2458.06  746.422459.945   756.5 2458.91   776.1 2460.38
   795.8 2465.12  806.362469.604   812.2 2472.13  839.042488.572   966.1  2562.7
   979.2  2566.5     989 2573.05    1025 2588.26  1041.4 2593.71  1087.2    2605
#Mann= 12 ,-1 , 0
       0     .06       0    5.14     .12       0   60.88     .06       0
  259.72     .12       0  293.07     .06       0  294.34     .12       0
   424.2    .045       0  440.05     .12       0  481.29     .06       0
  746.42     .12       0  806.36    .016       0  839.04     .12       0
#XS Ineff= 2 , 0
                          746.51         2461.33
Permanent Ineff=
       F       F
Bank Sta=424.2,440.05
XS Rating Curve= 0 ,0
Exp/Cntr=0.3,0.1

Type RM Length L Ch R = 1 ,36834.9 ,303.9,303,301.3
XS GIS Cut Line= 2
      2154086.72       240011.51     2154049.531      241041.862
#Sta/Elev= 30
       0 2462.75   15.872463.086   59.582462.383  117.562460.115   209.5 2457.64
   261.8 2458.41  554.012455.233     563 2455.24   576.1 2452.44   585.9  2454.2
   605.5 2454.73  623.572451.131   628.4 2450.37   638.2 2451.12   644.8 2453.96
   657.9 2463.79   667.7 2464.92     671 2466.82  680.582475.573  724.292501.061
   752.8 2518.17   765.9 2523.85     779 2531.61   798.6  2540.3   837.9 2554.63
   847.7 2559.27   857.6 2560.92   877.2 2568.74   942.6 2589.04    1031 2610.84
#Mann= 9 ,-1 , 0
       0     .12       0   15.87     .06       0   59.58     .12       0
  117.56     .06       0  554.01     .12       0  623.57    .045       0
   638.2     .12       0  680.58    .016       0  724.29     .12       0
#XS Ineff= 2 , 0
          443.64 2457.94
Permanent Ineff=
       F       F
Bank Sta=623.57,638.2
XS Rating Curve= 0 ,0
Exp/Cntr=0.3,0.1

Type RM Length L Ch R = 1 ,36531.9 ,345.5,350,352.7
XS GIS Cut Line= 3
     2153753.435      240179.426     2153762.719      240634.332
     2153772.004      241089.237
#Sta/Elev= 30
       0 2463.86    22.9 2460.71   55.462460.474    75.3 2460.74   120.82458.922
   287.32454.669  356.872453.179  418.212453.694   428.8 2452.94   445.2 2449.99
   451.7 2449.76   458.3 2449.93   471.4 2453.87   484.5 2455.38   494.3 2460.55
   504.1 2461.87   507.4 2463.41   513.9 2468.52   523.7 2473.82   549.9 2486.07
   572.8 2494.48   592.5  2500.2   628.5 2506.96   680.9 2512.87   736.5 2512.71
   762.7 2514.33   792.2 2522.68   808.5 2529.53   890.4 2556.96     910 2560.76
#Mann= 8 ,-1 , 0
       0     .12       0   55.46    .016       0   120.8     .06       0
   287.3     .12       0  356.87     .06       0  418.21     .12       0
   445.2    .045       0   458.3     .12       0
Bank Sta=445.2,458.3
XS Rating Curve= 0 ,0
Exp/Cntr=0.3,0.1

Type RM Length L Ch R = 1 ,36181.9 ,352.5,350,347.4
XS GIS Cut Line= 3
     2153493.767      240149.689     2153419.787       240597.78
     2153367.589      241054.067
#Sta/Elev= 30
       0 2457.07   19.832456.914   49.76  2456.6     134 2457.67   225.4 2456.57
   254.8  2455.1   297.3 2451.42  348.92 2451.15  412.79 2451.93  432.272452.125
   444.4 2447.91   450.9  2446.9   460.7  2447.9   477.1 2449.08     487  2452.1
   500.1 2454.57   509.9 2459.01   526.3 2469.64   549.3 2480.07   572.2 2488.77
   595.2  2495.8   614.9 2502.94   667.4  2515.1   700.2 2524.59   746.1 2536.62
   762.5 2541.82   782.2 2546.16   798.6 2548.69   841.2 2558.86   913.4  2572.5
#Mann= 8 ,-1 , 0
       0    .016       0   19.83     .12       0   49.76     .06       0
  348.92     .12       0  412.79     .06       0  432.27     .12       0
   444.4    .045       0   460.7     .12       0
#XS Ineff= 2 , 0
          319.31  2453.9
Permanent Ineff=
       F       F
Bank Sta=444.4,460.7
XS Rating Curve= 0 ,0
Exp/Cntr=0.3,0.1

Type RM Length L Ch R = 1 ,35831.9 ,455.7,454.4,452.9
XS GIS Cut Line= 3
     2153089.913      240135.964     2153070.984      240590.402
     2153065.143      241046.312
#Sta/Elev= 30
       0 2457.19    32.7 2455.74   189.8 2453.08   232.3 2450.63   291.2 2451.93
   333.8  2448.5   425.4 2449.26  433.252448.802   441.7 2446.74   447.3 2446.11
   454.8 2445.65     4602446.107   474.5 2449.42   481.1 2453.44   490.9 2461.32
   510.6 2474.17   556.5 2500.62   592.6 2519.35   635.2 2538.21     691 2561.86
   707.4 2566.37   717.2 2568.35   723.8    2569   740.2 2568.07   766.4 2562.68
   786.1 2557.42   818.9 2546.44     855 2535.44   871.4 2531.71   910.8 2524.51
#Mann= 4 ,-1 , 0
       0     .06       0  433.25     .12       0   447.3    .045       0
     460     .12       0
#XS Ineff= 2 , 0
          291.02 2454.66
Permanent Ineff=
       F       F
Bank Sta=447.3,460
XS Rating Curve= 0 ,0
Exp/Cntr=0.3,0.1

Type RM Length L Ch R = 1 ,35377.6 ,245.7,245.6,247.1
XS GIS Cut Line= 2
      2152656.04      240055.262     2152680.103      241017.799
#Sta/Elev= 30
       0 2460.32    62.2 2458.48   104.8 2455.86     190 2453.13     226 2448.74
   347.2 2447.52   383.2 2445.48   402.8 2446.26  412.012444.091   415.9 2443.48
   425.9 2444.05   438.8 2445.49   451.9 2445.91   478.1 2453.83   481.4  2455.6
   491.2 2463.13   514.2 2476.34   527.3 2482.23   553.5 2495.88   582.9 2509.61
   609.1 2521.19   651.7 2537.96   671.4 2544.18   681.2 2548.25   700.8 2554.06
   730.3 2561.66   759.8 2567.92   818.7 2575.21   864.6 2578.54   962.8 2589.22
#Mann= 3 ,-1 , 0
       0     .12       0  412.01    .045       0   425.9     .12       0
#XS Ineff= 2 , 0
          265.36 2450.44
Permanent Ineff=
       F       F
Bank Sta=412.01,425.9
XS Rating Curve= 0 ,0
Exp/Cntr=0.3,0.1