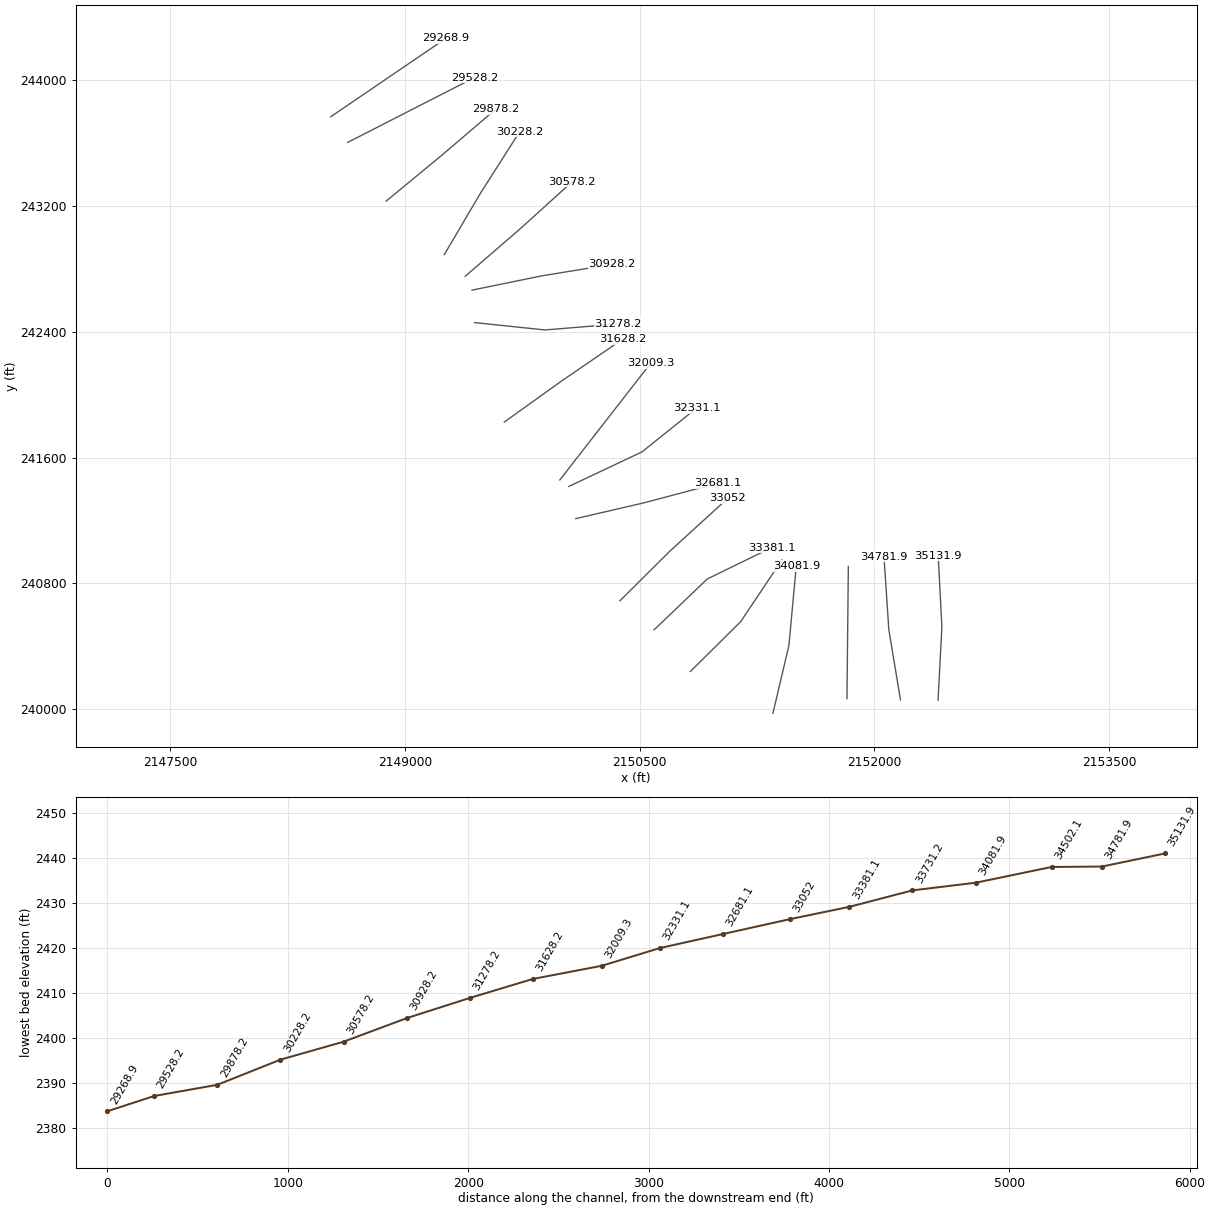
HEC-RAS study LAURELCK3.prj: LAURELCK3

--- LAURELCK3.g01 (geometry) --- (continued)

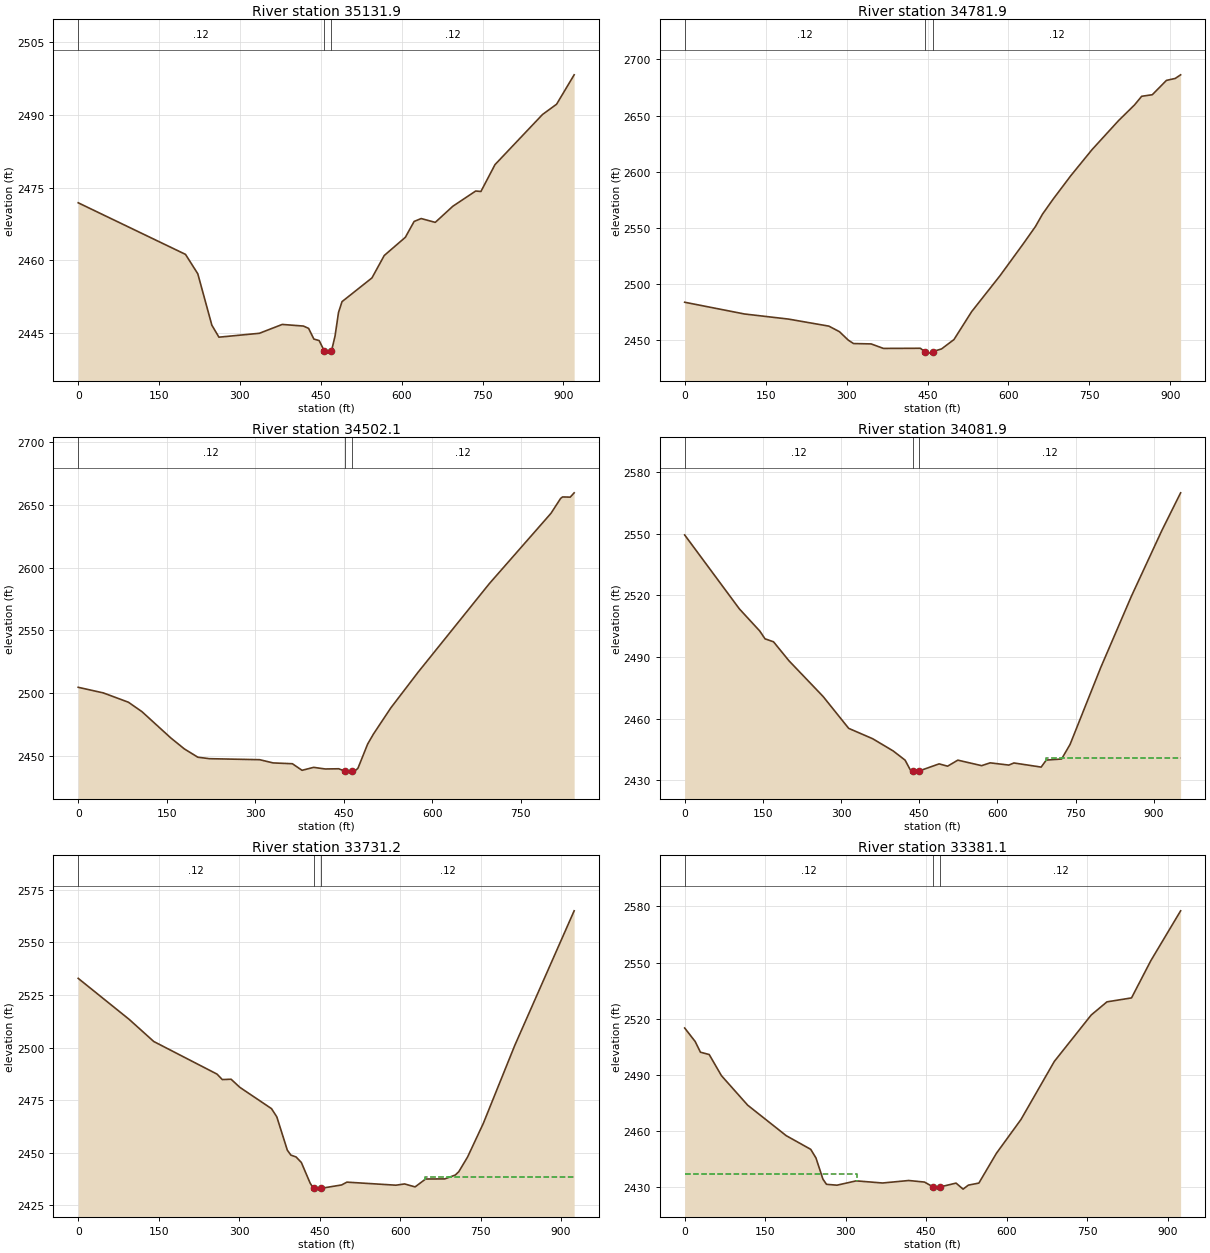
Type RM Length L Ch R = 1 ,35131.9 ,344.6,350,349.6
XS GIS Cut Line= 3
     2152406.993      240056.554     2152431.471      240522.391
     2152407.933      240975.086
#Sta/Elev= 30
       0 2471.86     199 2461.25   221.8 2457.26   247.9 2446.68     261 2444.22
     336 2445.02   378.4 2446.84   417.6 2446.51   427.3 2446.03   437.1 2443.83
   446.9 2443.52   456.7 2441.32   466.5 2440.94   469.7 2441.36   476.3 2444.43
   482.8 2449.32   489.3 2451.53   544.8 2456.41   567.6 2461.02   606.7 2464.76
     623 2468.02   636.1 2468.62   662.2 2467.83   694.8 2471.15   737.2 2474.28
   746.9 2474.19     773 2479.71   861.1 2490.02   887.2 2492.13   919.8 2498.18
#Mann= 3 ,-1 , 0
       0     .12       0   456.7    .045       0   469.7     .12       0
Bank Sta=456.7,469.7
XS Rating Curve= 0 ,0
Exp/Cntr=0.3,0.1

Type RM Length L Ch R = 1 ,34781.9 ,281,279.8,293.5
XS GIS Cut Line= 3
     2152166.803      240057.838      2152092.32      240504.757
     2152061.298      240969.588
#Sta/Elev= 30
       0 2483.42   110.8 2472.95   192.3  2468.4   267.3  2462.1   286.8 2457.15
   303.1 2449.64   312.9 2446.57   345.5 2446.25   368.3 2442.23   436.8 2442.36
   445.6 2439.07   453.1 2438.03   459.6  2439.4     476 2441.78     499 2450.14
   531.8 2475.06   584.3 2507.08     627 2535.29   649.9  2550.9     663 2561.97
   682.7 2575.36   715.5  2596.3   754.9  2619.6   804.1  2645.5   833.6 2659.45
   846.8 2667.14   866.5 2668.53   892.7 2681.31   909.1 2683.09     919 2686.29
#Mann= 3 ,-1 , 0
       0     .12       0   445.6    .045       0   459.6     .12       0
Bank Sta=445.6,459.6
XS Rating Curve= 0 ,0
Exp/Cntr=0.3,0.1

Type RM Length L Ch R = 1 ,34502.1 ,425.2,420.2,417.2
XS GIS Cut Line= 2
     2151824.758        240066.2     2151833.508      240906.232
#Sta/Elev= 30
       0  2504.7    42.5 2500.24      85 2492.82   107.9 2485.33   156.9 2464.35
   179.8 2455.63   202.7    2449   222.3 2447.84   307.3 2447.04   330.2 2444.47
   362.8 2443.82   379.2 2438.57   398.8 2440.94   418.4 2439.64   441.3 2439.81
   451.1 2438.01   457.6 2437.93   464.2 2438.08   470.7 2438.79     474 2440.38
   490.3  2459.5   500.1 2467.46   529.5 2488.28   575.3 2516.45   696.2 2587.15
   800.8 2643.26   817.2 2655.17   820.5 2656.33   833.5 2656.18   840.1 2659.61
#Mann= 3 ,-1 , 0
       0     .12       0   451.1    .045       0   464.2     .12       0
Bank Sta=451.1,464.2
XS Rating Curve= 0 ,0
Exp/Cntr=0.3,0.1

Type RM Length L Ch R = 1 ,34081.9 ,363.2,350.7,337.5
XS GIS Cut Line= 3
     2151351.501      239971.864      2151453.91      240405.755
     2151500.598      240909.337
#Sta/Elev= 30
       0 2549.35   104.9  2513.4   144.2 2502.58   154.1 2498.82   170.5 2497.36
     200 2488.17   265.5 2470.79   314.7 2455.25   360.6 2450.22   399.9 2444.29
   422.9  2439.8   432.7 2435.15   438.3 2434.57   449.1 2434.44  450.142434.541
   488.2 2437.97   504.5 2436.85   524.1 2439.78   569.8  2437.1   586.1 2438.47
     622 2437.38   631.8 2438.41     684  2436.4   693.8 2439.81   723.2 2440.33
   739.5 2447.45   798.2 2484.77   856.9 2519.39   915.7 2551.58   951.6 2569.85
#Mann= 3 ,-1 , 0
       0     .12       0   438.3    .045       0  450.14     .12       0
#XS Ineff= 2 , 0
                          693.05         2440.84
Permanent Ineff=
       F       F
Bank Sta=438.3,450.14
XS Rating Curve= 0 ,0
Exp/Cntr=0.3,0.1

Type RM Length L Ch R = 1 ,33731.2 ,349.5,350.1,339.2
XS GIS Cut Line= 3
     2150823.704      240238.194     2151145.401      240555.762
     2151408.926      240947.934
#Sta/Elev= 30
       0 2532.91      95 2513.42   140.8 2502.91   258.8  2487.4   268.6 2484.81
     285 2484.97   301.4  2481.1   360.3    2471   370.2  2467.1   389.8 2451.28
   396.4 2448.92   406.2 2448.02     416 2445.39   432.4 2435.56   438.9 2433.04
   442.2 2432.74     452 2433.09   491.1 2434.73   500.9 2436.06   592.2 2434.61
   608.4  2435.2     628  2433.8   647.6 2437.55   683.4  2437.6     703 2439.45
   709.5 2441.05   725.8 2447.99   755.1 2463.94   813.7 2500.98   924.5 2565.01
#Mann= 3 ,-1 , 0
       0     .12       0   438.9    .045       0     452     .12       0
#XS Ineff= 2 , 0
                          645.97         2438.41
Permanent Ineff=
       F       F
Bank Sta=438.9,452
XS Rating Curve= 0 ,0
Exp/Cntr=0.3,0.1

Type RM Length L Ch R = 1 ,33381.1 ,328.4,329.1,335.1
XS GIS Cut Line= 3
     2150591.944      240503.678     2150932.274      240827.556
     2151341.213      241025.925
#Sta/Elev= 30
       0 2515.08    19.6 2507.86    29.4 2502.16    45.7 2500.93    68.5 2489.66
   117.4  2473.9   189.2 2457.63   234.9 2450.33   244.7 2445.72   257.7  2434.4
   264.3 2431.66   283.8 2431.19   319.7  2433.5   368.7 2432.36   417.6 2433.69
     447 2432.85   462.3 2430.38   476.4 2430.29   505.8  2432.3   518.9 2429.09
   528.7 2431.22   548.3 2432.32     581 2448.21   626.8 2466.27   688.9 2497.24
   757.6    2522     787 2529.04   832.8 2531.14   868.7 2550.97   924.3 2577.62
#Mann= 3 ,-1 , 0
       0     .12       0   462.3    .045       0   476.4     .12       0
#XS Ineff= 2 , 0
          321.98  2437.3
Permanent Ineff=
       F       F
Bank Sta=462.3,476.4
XS Rating Curve= 0 ,0
Exp/Cntr=0.3,0.1

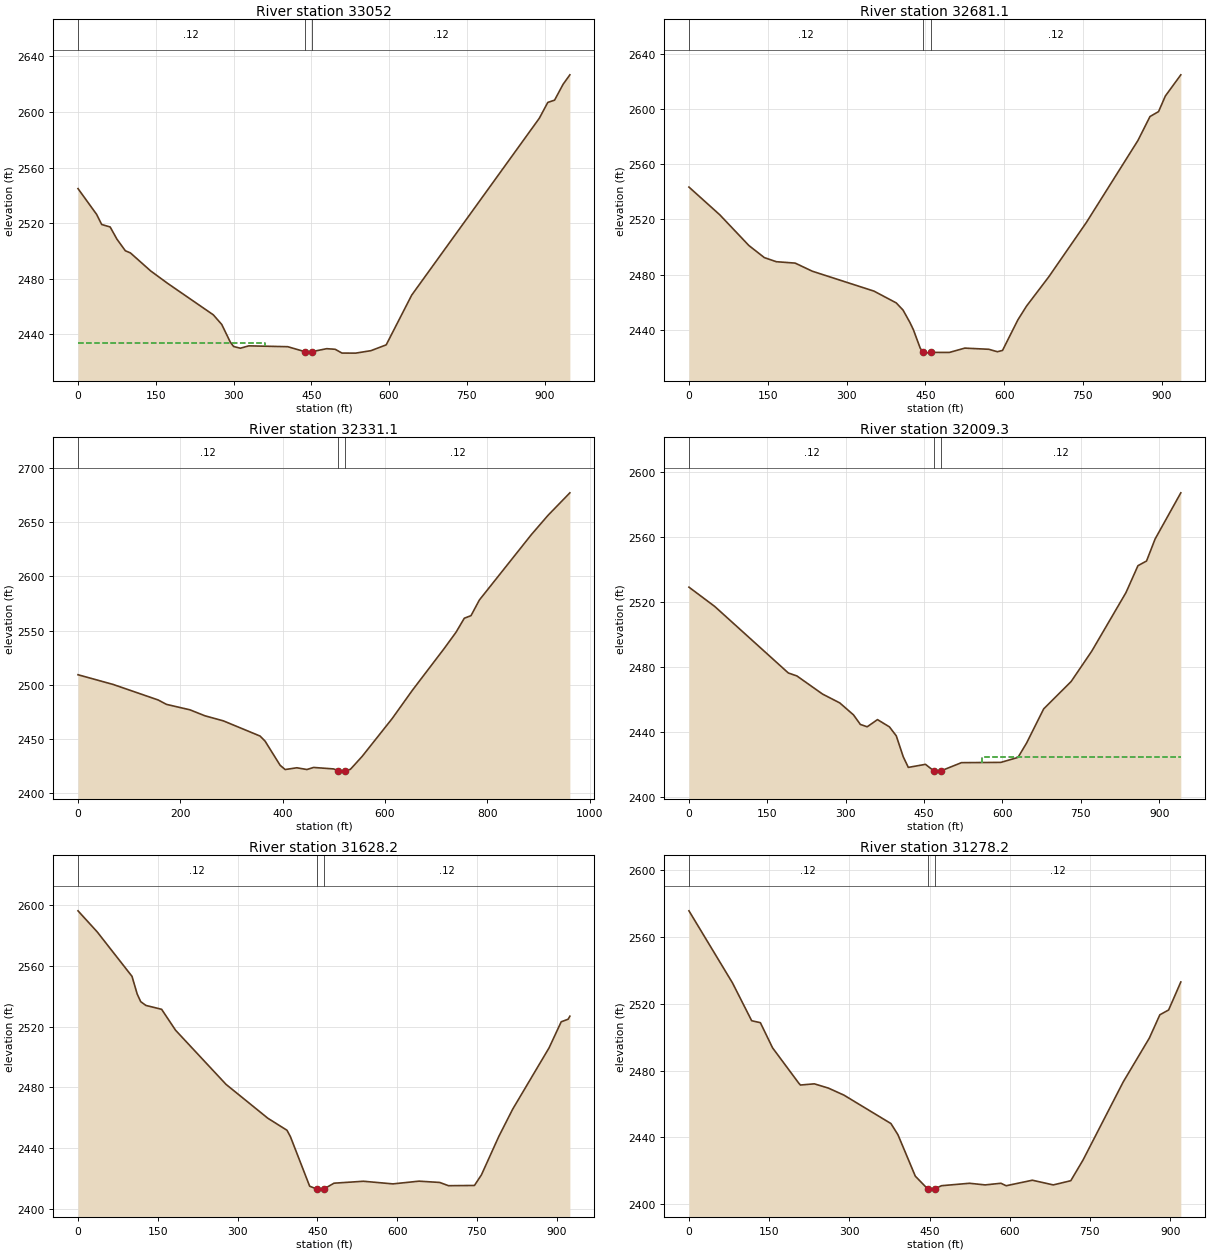
Type RM Length L Ch R = 1 ,33052   ,382.9,370.9,358.7
XS GIS Cut Line= 3
     2150373.866      240688.646     2150691.505      241003.039
     2151062.895      241340.638
#Sta/Elev= 30
       0 2544.83    35.9 2526.28    45.7 2518.99      62 2517.22      75 2508.49
    91.3 2500.07   101.1 2498.54   140.3 2485.51   172.9  2476.6     261 2453.94
   277.3 2446.99   293.6 2434.42   300.1 2431.13   313.2  2429.9   329.5  2431.6
   404.5 2430.99   437.1 2427.47  451.84 2427.46   479.7 2429.56   496.1 2429.12
   509.2  2426.4   535.5 2426.36     565 2428.12   594.5 2432.32   643.7 2468.14
   889.8 2595.48   906.2  2606.9   919.3 2608.55   935.7 2619.96   948.8 2626.78
#Mann= 3 ,-1 , 0
       0     .12       0   437.1    .045       0  451.84     .12       0
#XS Ineff= 2 , 0
           361.5 2433.97
Permanent Ineff=
       F       F
Bank Sta=437.1,451.84
XS Rating Curve= 0 ,0
Exp/Cntr=0.3,0.1

Type RM Length L Ch R = 1 ,32681.1 ,344.6,350,357.5
XS GIS Cut Line= 3
     2150091.573      241211.262     2150530.049      241312.482
     2151000.253      241436.605
#Sta/Elev= 30
       0 2543.35    58.7 2523.26   114.1 2501.01   143.5 2492.26   166.3 2489.28
   202.2 2488.27   234.8  2482.4   352.2 2467.98   394.6 2459.44   407.6 2454.22
   420.7 2445.22   427.2 2440.04   440.2 2426.69   445.52423.667     450 2423.06
   459.8  2423.6   495.7 2423.56   525.1 2426.69   570.8 2425.84   587.1 2424.08
   596.9 2425.02   626.2 2447.22   642.6 2457.13     685 2478.36   756.8 2517.88
   854.7 2577.12   877.6 2594.44   893.9 2598.02   906.9 2609.34   936.3 2624.66
#Mann= 3 ,-1 , 0
       0     .12       0   445.5    .045       0   459.8     .12       0
Bank Sta=445.5,459.8
XS Rating Curve= 0 ,0
Exp/Cntr=0.3,0.1

Type RM Length L Ch R = 1 ,32331.1 ,311,321.8,326.4
XS GIS Cut Line= 3
     2150047.045      241416.186      2150513.91      241635.606
     2150862.135      241913.416
#Sta/Elev= 30
       0 2509.09    68.6 2500.12   156.7 2485.75     173 2481.67   218.8 2476.65
   248.1 2471.12     284 2466.45   355.9 2452.37   365.7 2447.65     395 2425.37
   404.8 2421.42   427.7 2423.05   447.3 2421.44   460.4 2423.35   499.5 2421.99
   508.4 2420.45   515.9 2419.95   522.4 2420.53   532.2 2421.55   555.2  2433.5
   614.1 2468.63   653.4 2494.66   715.7 2533.38   738.6 2548.25     755 2561.36
   768.1 2563.74   784.4 2578.19     886 2638.65   918.7 2656.58   961.3 2677.33
#Mann= 3 ,-1 , 0
       0     .12       0   508.4    .045       0   522.4     .12       0
Bank Sta=508.4,522.4
XS Rating Curve= 0 ,0
Exp/Cntr=0.3,0.1

Type RM Length L Ch R = 1 ,32009.3 ,387.5,381.1,374
XS GIS Cut Line= 2
     2149989.375      241457.503     2150569.085      242199.094
#Sta/Elev= 30
       0    2529    49.2 2517.19   190.2 2476.29   206.6 2474.47   255.8 2463.31
   288.6 2457.92   314.9 2450.56     328  2444.7   341.1 2443.25   360.8 2447.66
   383.7 2443.19   396.8 2437.67     410 2424.92   419.8 2418.31   452.6 2420.19
     469 2416.08   475.6 2416.02   482.1 2416.16   521.5 2421.22   596.9 2421.39
   629.7 2424.44   646.1 2433.25   678.9 2454.27   731.4 2471.05   770.7 2489.62
   836.3 2525.64   859.3 2542.19   875.7 2545.06   892.1 2558.59   941.3 2586.93
#Mann= 3 ,-1 , 0
       0     .12       0     469    .045       0   482.1     .12       0
#XS Ineff= 2 , 0
                          560.28         2424.45
Permanent Ineff=
       F       F
Bank Sta=469,482.1
XS Rating Curve= 0 ,0
Exp/Cntr=0.3,0.1

Type RM Length L Ch R = 1 ,31628.2 ,366,350,338
XS GIS Cut Line= 3
     2149634.311      241825.874     2150002.192      242088.208
     2150392.935      242354.531
#Sta/Elev= 30
       0 2596.27      36 2582.45   101.5 2553.16   111.3 2541.48   117.9 2536.49
   127.7    2534   157.2 2531.46   183.4 2517.69   278.3 2482.05   356.9 2459.76
   392.9 2451.85   399.4 2447.59   435.5 2415.03   448.6 2413.24   455.1 2413.11
  462.512413.249   481.2 2417.01   536.6 2418.29   592.1 2416.56     641 2418.35
   680.1  2417.5   696.4 2415.37   745.3 2415.52   758.4 2422.48     791 2447.71
   817.1 2465.68   885.6 2506.09   908.4 2523.23   921.4 2524.93   924.7 2526.92
#Mann= 3 ,-1 , 0
       0     .12       0   448.6    .045       0  462.51     .12       0
Bank Sta=448.6,462.51
XS Rating Curve= 0 ,0
Exp/Cntr=0.3,0.1

Type RM Length L Ch R = 1 ,31278.2 ,342.9,350,351.5
XS GIS Cut Line= 3
     2149444.116      242458.868     2149894.444       242411.94
     2150360.174      242450.051
#Sta/Elev= 30
       0 2575.78    81.4 2532.57   117.3 2509.88   133.6  2508.7   156.4 2493.61
   205.2 2472.53   208.5 2471.31   234.5 2472.03   260.6  2469.5   289.9 2465.26
   377.8 2448.21   390.9 2441.52   423.4 2416.66   446.2 2409.13   452.8 2408.89
   460.3 2409.17   472.4 2410.94   524.7  2412.4   554.1 2411.42   583.5 2412.41
   593.3 2410.92   642.3 2414.23   681.5 2411.42   714.2 2413.94   737.1 2426.35
   812.2 2473.14   861.2 2499.52   880.8 2513.45   897.2 2516.33     920 2533.12
#Mann= 3 ,-1 , 0
       0     .12       0   446.2    .045       0   460.3     .12       0
Bank Sta=446.2,460.3
XS Rating Curve= 0 ,0
Exp/Cntr=0.3,0.1

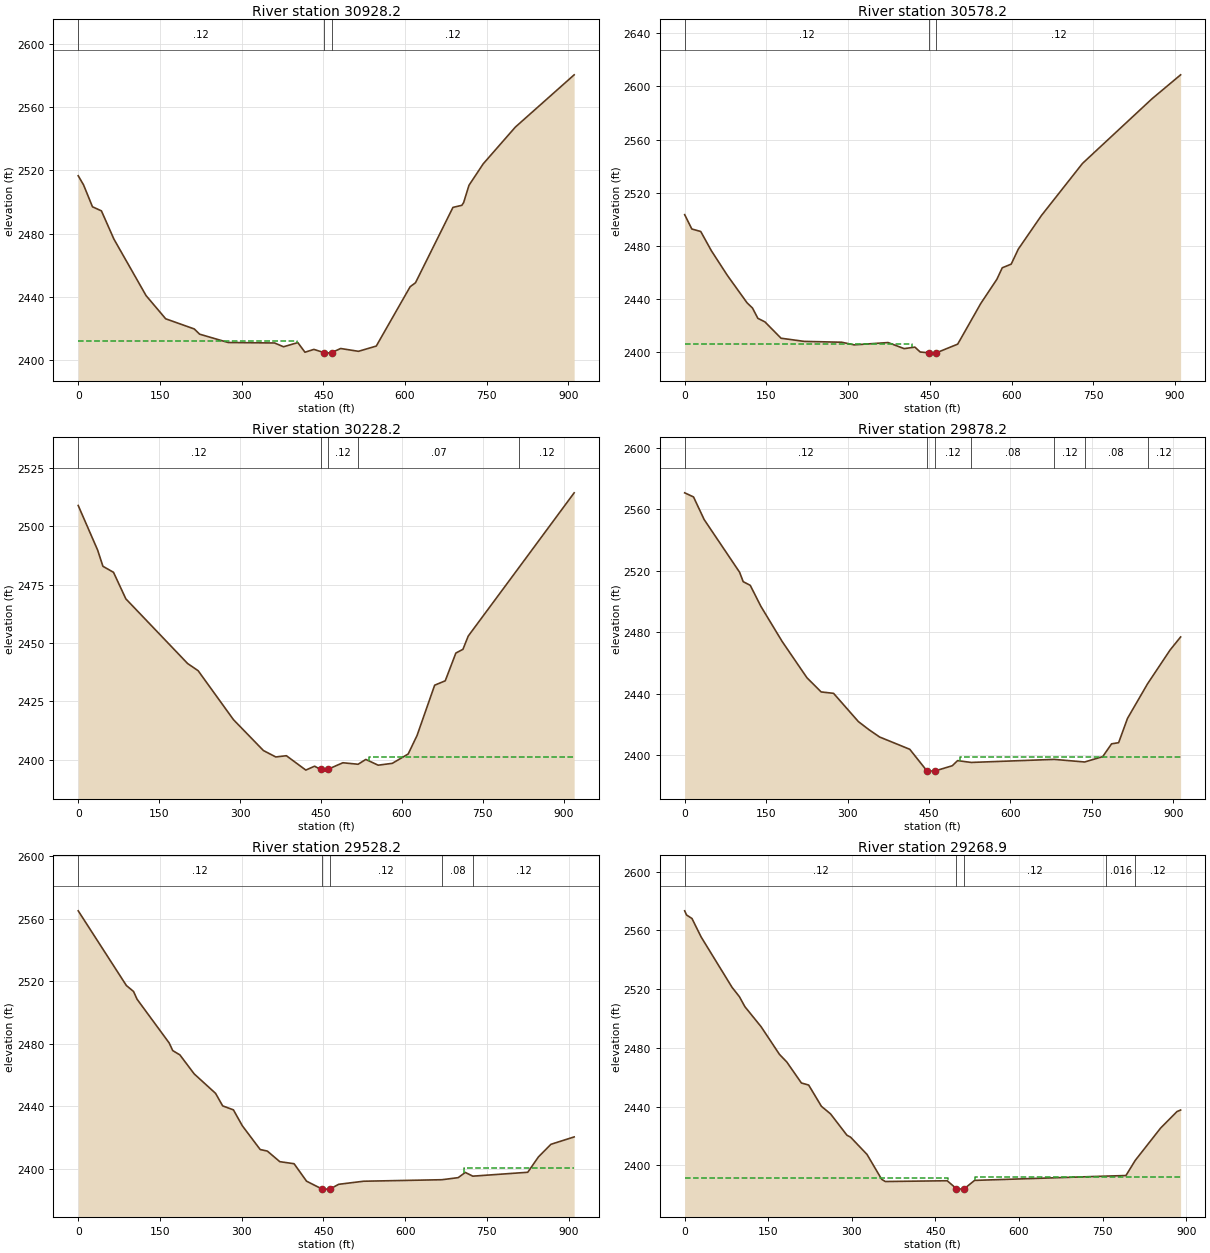
Type RM Length L Ch R = 1 ,30928.2 ,337.7,350,362.5
XS GIS Cut Line= 3
     2149427.545      242665.247     2149873.969      242756.224
     2150323.018      242829.212
#Sta/Elev= 30
       0 2516.68     9.8 2510.89    26.2 2497.03    42.6 2494.45    65.6 2476.55
   124.6 2440.81   160.6 2426.14     213 2419.72   222.9 2416.41   275.3 2411.13
   360.6 2410.83   376.9 2408.44   403.2 2411.07   416.3 2404.98   432.7 2406.78
  451.062404.739   455.6 2404.41   465.4 2404.75   481.8 2407.34   514.5 2405.56
   547.2 2408.88   609.4 2446.44   619.2 2448.94     688 2496.65   704.3 2497.96
   707.6  2499.7   717.4 2510.62   743.6 2524.24   802.5 2547.46   910.5 2580.55
#Mann= 3 ,-1 , 0
       0     .12       0  451.06    .045       0   465.4     .12       0
#XS Ineff= 2 , 0
          402.53 2411.81
Permanent Ineff=
       F       F
Bank Sta=451.06,465.4
XS Rating Curve= 0 ,0
Exp/Cntr=0.3,0.1

Type RM Length L Ch R = 1 ,30578.2 ,342.5,350,355.7
XS GIS Cut Line= 3
     2149384.326      242753.426     2149729.685      243050.175
     2150067.739       243354.82
#Sta/Elev= 30
       0 2503.45    13.1 2492.67    29.5 2490.78    49.1 2476.23    78.6 2457.58
   114.6 2437.03   124.5 2433.14   134.3 2425.41   147.4 2422.68   176.9  2410.4
   219.5 2408.02   288.3 2407.38   311.2  2405.4   373.4 2407.14   402.9 2402.57
   422.6 2403.71   432.4 2400.02   447.8 2399.46   455.3 2399.18   461.9  2399.4
   501.2 2405.95   543.7 2436.68   573.2 2454.85     583 2463.45   599.4 2466.21
   612.5 2477.56     655 2502.87   730.3 2542.06     858 2590.78   910.4 2608.77
#Mann= 3 ,-1 , 0
       0     .12       0   447.8    .045       0   461.9     .12       0
#XS Ineff= 2 , 0
          417.98 2406.21
Permanent Ineff=
       F       F
Bank Sta=447.8,461.9
XS Rating Curve= 0 ,0
Exp/Cntr=0.3,0.1

Type RM Length L Ch R = 1 ,30228.2 ,357.6,350,343.1
XS GIS Cut Line= 3
     2149250.663       242891.38     2149482.166      243282.486
     2149732.798      243673.673
#Sta/Elev= 30
       0 2508.79      36 2489.72    45.8  2482.8    65.4 2480.22    88.3 2468.87
   202.7 2441.23   222.3 2438.13   287.7 2417.21   343.3 2403.99   366.2 2401.26
   385.8 2401.79   421.8 2395.65   438.1 2397.31  449.042395.929   454.5  2395.2
     462 2395.91   490.5 2398.78  518.652398.137     533  2400.2   555.9 2397.74
   582.1 2398.53   611.5 2402.52   627.9 2410.41   660.6 2431.95   680.2 2433.82
   699.9  2445.7     713 2447.28   722.8 2452.95   817.32482.411   919.1 2514.21
#Mann= 5 ,-1 , 0
       0     .12       0  449.04    .045       0     462     .12       0
  518.65     .07       0   817.3     .12       0
#XS Ineff= 2 , 0
                          538.56         2401.18
Permanent Ineff=
       F       F
Bank Sta=449.04,462
XS Rating Curve= 0 ,0
Exp/Cntr=0.3,0.1

Type RM Length L Ch R = 1 ,29878.2 ,354.7,350,344.6
XS GIS Cut Line= 3
     2148880.001      243232.476     2149230.882      243520.436
     2149581.333      243818.008
#Sta/Elev= 30
       0 2570.69    16.3 2568.01    35.9 2553.29   101.2 2519.02   107.8 2512.89
   120.8 2510.51   140.4 2496.84   179.6 2473.97   225.3 2450.36   251.4 2441.15
   274.3 2440.24     320 2421.86   339.6 2416.56   359.2 2411.81   414.7 2403.83
   446.4 2389.75   447.4 2389.62   461.4 2389.76     493 2393.12   502.8 2396.46
  527.912395.272   680.72397.262   736.92395.568   770.2 2399.06   786.5 2407.38
   799.5 2408.12   815.8 2423.91  852.812446.456   894.1 2468.33   913.7 2476.92
#Mann= 7 ,-1 , 0
       0     .12       0   446.4    .045       0   461.4     .12       0
  527.91     .08       0   680.7     .12       0   736.9     .08       0
  852.81     .12       0
#XS Ineff= 2 , 0
                          507.42         2398.64
Permanent Ineff=
       F       F
Bank Sta=446.4,461.4
XS Rating Curve= 0 ,0
Exp/Cntr=0.3,0.1

Type RM Length L Ch R = 1 ,29528.2 ,254.3,259.3,262.8
XS GIS Cut Line= 3
     2148633.678      243605.646     2149039.157      243812.074
     2149444.635      244018.501
#Sta/Elev= 30
       0 2565.08    88.4 2517.31   101.5 2513.52     108 2508.56   166.9  2480.6
   173.5  2475.7   186.6 2472.96   212.8 2460.82     252 2448.39   265.1 2440.36
   284.8 2437.82   301.2 2427.62   333.9 2412.47     347 2411.47   369.9  2404.7
   396.1 2403.38     419 2392.21   447.5  2387.2     455 2387.14   462.5 2387.29
   477.9 2390.22   523.7 2392.19  667.422393.155   697.2 2394.48   710.3 2397.81
  724.022395.431   824.9 2397.92   844.5 2407.75   867.4  2415.8     910 2420.52
#Mann= 5 ,-1 , 0
       0     .12       0   447.5    .045       0   462.5     .12       0
  667.42     .08       0  724.02     .12       0
#XS Ineff= 2 , 0
                          707.97          2400.4
Permanent Ineff=
       F       F
Bank Sta=447.5,462.5
XS Rating Curve= 0 ,0
Exp/Cntr=0.3,0.1

Type RM Length L Ch R = 1 ,29268.9 ,20.4,18.5,17.8
XS GIS Cut Line= 2
     2148524.743      243768.669     2149261.505        244267.8
#Sta/Elev= 30
       0 2573.36     3.3 2570.55    13.1 2568.13    29.4 2555.63    85.1 2521.19
    98.2 2514.87     108 2508.09   137.4 2494.27   170.1 2475.56   183.2  2470.4
   209.4 2456.09   222.5 2454.66   245.4 2440.16   261.7 2435.04   291.2 2420.47
   297.7 2419.16   327.2  2407.4   353.4  2390.5   359.9 2388.94   471.1 2389.47
   487.5 2384.12   497.3 2383.76   501.6 2383.99   520.2 2389.71  755.83 2392.62
   791.8 2393.02  808.452403.326   853.9 2425.31   883.4 2436.61   889.9 2437.65
#Mann= 5 ,-1 , 0
       0     .12       0   487.5    .045       0   501.6     .12       0
  755.83    .016       0  808.45     .12       0
#XS Ineff= 2 , 0
          471.79 2391.62  521.75         2391.76
Permanent Ineff=
       F       F
Bank Sta=487.5,501.6
XS Rating Curve= 0 ,0
Exp/Cntr=0.3,0.1