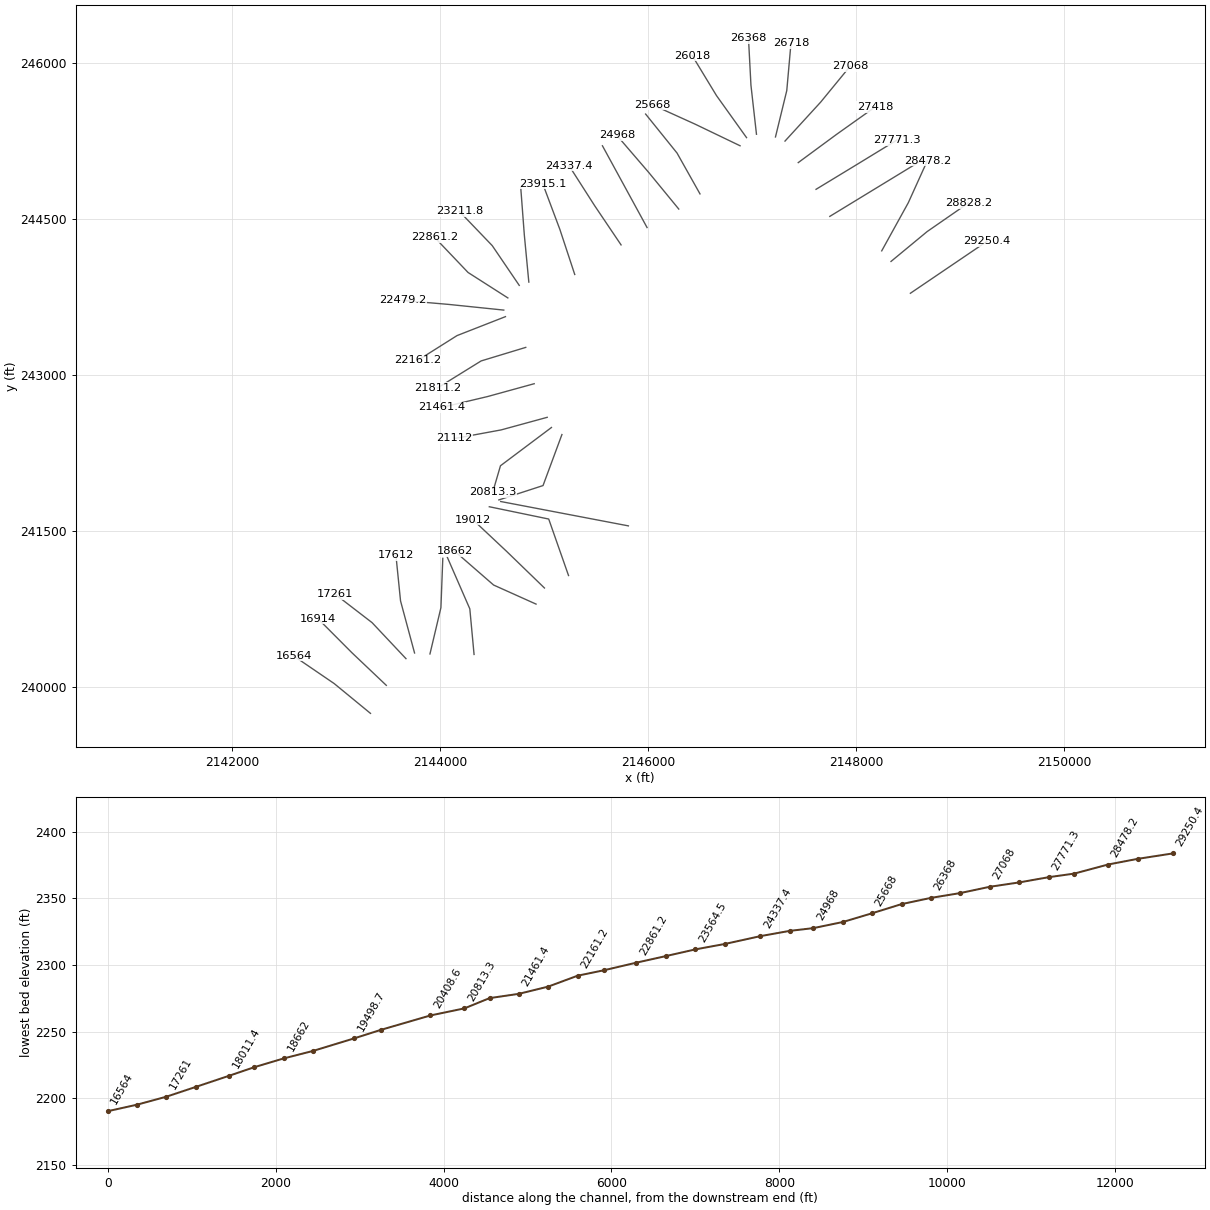
HEC-RAS study LAURELCK3.prj: LAURELCK3

--- LAURELCK3.g01 (geometry) --- (continued)

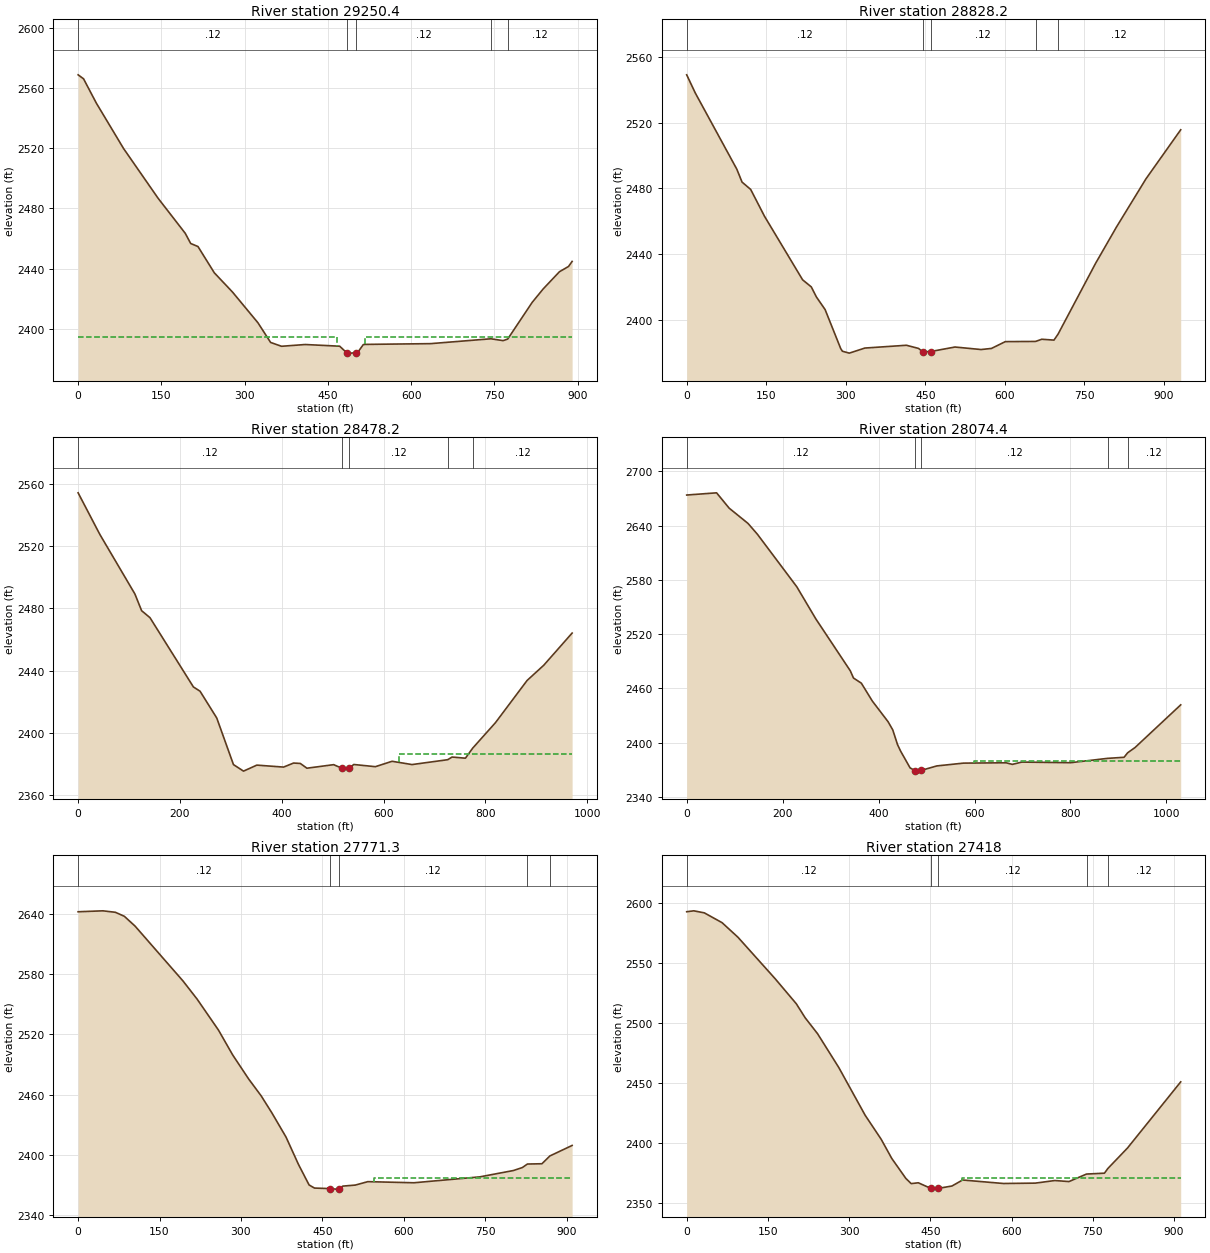
Type RM Length L Ch R = 1 ,29250.4 ,419.6,422.2,421.9
XS GIS Cut Line= 2
     2148519.318       243786.03      2149256.08      244285.162
#Sta/Elev= 30
       0    2569     9.8 2566.35    32.7 2550.24    81.8 2519.97     144 2486.86
     193 2463.48   202.8 2456.69   215.9 2454.68   245.4 2437.16   278.1 2424.37
   323.9 2403.93   346.8  2390.8   366.4 2388.26     409 2389.43   471.1 2388.32
   484.2 2383.84   490.8  2383.7   500.6 2383.87   503.8 2384.27   513.7 2389.36
   516.9 2389.51   634.7 2390.01  743.642393.254   765.6 2392.01  773.872393.088
   817.9 2417.47   837.6 2426.37     867 2437.88   883.4  2441.4   889.9 2444.77
#Mann= 5 ,-1 , 0
       0     .12       0   484.2    .045       0   500.6     .12       0
  743.64    .016       0  773.87     .12       0
#XS Ineff= 2 , 0
          466.46 2394.34  517.03         2394.76
Permanent Ineff=
       F       F
Bank Sta=484.2,500.6
XS Rating Curve= 0 ,0
Exp/Cntr=0.3,0.1

Type RM Length L Ch R = 1 ,28828.2 ,341.3,350,361.8
XS GIS Cut Line= 3
     2148333.053      244091.647     2148680.237      244378.447
     2149076.104      244652.557
#Sta/Elev= 30
       0 2549.18    16.3 2538.04    94.6 2491.64   104.4  2483.8   120.7 2479.33
   146.8 2462.96   218.6 2424.28     235 2419.94   244.7 2413.78   261.1 2406.11
   290.4 2382.43   293.7 2380.74   306.7 2379.59   336.1 2382.68   414.4 2384.38
   437.3 2382.46  444.862380.448   460.2 2380.56     506 2383.31   555.1 2381.78
   574.8 2382.44     601  2386.6  657.992386.713   669.8 2388.05   692.7 2387.52
  700.382391.124   771.3 2434.34   810.6 2456.42   866.3 2485.82   931.8 2515.69
#Mann= 5 ,-1 , 0
       0     .12       0  444.86    .045       0   460.2     .12       0
  657.99    .016       0  700.38     .12       0
Bank Sta=444.86,460.2
XS Rating Curve= 0 ,0
Exp/Cntr=0.3,0.1

Type RM Length L Ch R = 1 ,28478.2 ,414.5,403.8,389.5
XS GIS Cut Line= 3
     2148243.732      244193.305     2148499.205      244655.578
     2148681.617       245058.17
#Sta/Elev= 30
       0 2554.37    42.6 2527.67   111.5 2489.33   124.7 2478.57   141.1 2474.09
   226.4 2429.53   239.5 2426.77   272.3 2409.53   305.1 2379.58   324.8 2375.38
     351 2379.24   403.5 2377.98   423.2 2380.58   436.3 2380.32   449.4 2377.26
   501.9 2379.54   518.3 2377.19  532.332377.182   541.3 2379.65   583.8 2378.24
   616.6 2381.71   655.8  2379.6  725.852382.725   734.4 2384.44   760.6  2383.7
  775.052390.214   819.6 2406.53   881.8  2433.7   914.5 2443.49   970.2 2464.18
#Mann= 5 ,-1 , 0
       0     .12       0   518.3    .045       0  532.33     .12       0
  725.85    .016       0  775.05     .12       0
#XS Ineff= 2 , 0
                          630.55         2386.32
Permanent Ineff=
       F       F
Bank Sta=518.3,532.33
XS Rating Curve= 0 ,0
Exp/Cntr=0.3,0.1

Type RM Length L Ch R = 1 ,28074.4 ,302.7,303.1,301.5
XS GIS Cut Line= 2
     2147744.914      244524.496     2148624.323      245060.454
#Sta/Elev= 30
       0 2673.69    62.3 2676.13    88.6 2659.15   127.9 2642.28   147.6 2630.23
   229.6 2572.24   268.9 2537.06   341.1  2479.4   347.7 2471.44   364.1 2465.75
     387 2445.99   419.8 2423.18   429.6 2414.12   439.5 2397.89     446 2390.64
   465.7 2372.13   475.6 2369.18   482.1 2368.55   488.7 2369.34   521.5 2374.31
   577.2  2377.4   665.8 2377.77   678.9 2376.01   698.6 2378.55   800.3 2377.86
  877.642382.674   911.8 2383.84  919.182388.776   934.8 2394.69  1029.9  2441.8
#Mann= 5 ,-1 , 0
       0     .12       0   475.6    .045       0   488.7     .12       0
  877.64    .016       0  919.18     .12       0
#XS Ineff= 2 , 0
                           598.8          2379.4
Permanent Ineff=
       F       F
Bank Sta=475.6,488.7
XS Rating Curve= 0 ,0
Exp/Cntr=0.3,0.1

Type RM Length L Ch R = 1 ,27771.3 ,351,353.3,354.3
XS GIS Cut Line= 3
     2147612.508       244784.47     2148001.461      245020.569
     2148389.703      245257.829
#Sta/Elev= 30
       0  2642.3    45.8 2643.23    68.7 2641.76    85.1  2637.8   104.8 2628.07
   193.1  2573.4   219.3 2555.18   258.6 2524.34   284.8 2499.55   314.2 2475.62
   337.2 2458.82   356.8 2441.99     383 2417.74   405.9 2390.53   425.5 2370.01
   435.4 2366.94   464.8 2366.38   474.6 2365.88  479.922366.435   487.7 2368.89
   510.6 2369.91   533.6 2373.33   618.7 2372.22   739.8 2378.09     802 2384.43
   818.4 2387.41  827.562390.878   854.4 2391.18  869.062398.947     910 2409.42
#Mann= 5 ,-1 , 0
       0     .12       0   464.8    .045       0  479.92     .12       0
  827.56    .016       0  869.06     .12       0
#XS Ineff= 2 , 0
                          544.62         2377.36
Permanent Ineff=
       F       F
Bank Sta=464.8,479.92
XS Rating Curve= 0 ,0
Exp/Cntr=0.3,0.1

Type RM Length L Ch R = 1 ,27418   ,345.3,350,355.8
XS GIS Cut Line= 3
     2147441.441      245041.086     2147809.534      245312.047
     2148180.666       245575.65
#Sta/Elev= 30
       0 2593.06    13.1 2593.82    32.6 2592.12    65.3 2583.96    94.7 2571.79
   163.2 2537.32   202.4 2516.39   218.7 2504.75   241.6 2491.47   280.8 2463.32
   329.7 2423.37   359.1 2403.51   378.7  2387.5   404.8  2370.8   414.6 2366.52
   427.7 2367.22   450.5 2362.61   457.1 2361.93   464.6 2362.56   489.8 2364.52
   509.5 2369.53   584.8 2366.63   643.7 2366.93   679.8 2369.09     706 2368.23
  738.322374.489   771.5 2375.22  777.682379.084     814 2396.17   912.3  2451.3
#Mann= 5 ,-1 , 0
       0     .12       0   450.5    .045       0   464.6     .12       0
  738.32    .016       0  777.68     .12       0
#XS Ineff= 2 , 0
                          507.55         2371.43
Permanent Ineff=
       F       F
Bank Sta=450.5,464.6
XS Rating Curve= 0 ,0
Exp/Cntr=0.3,0.1

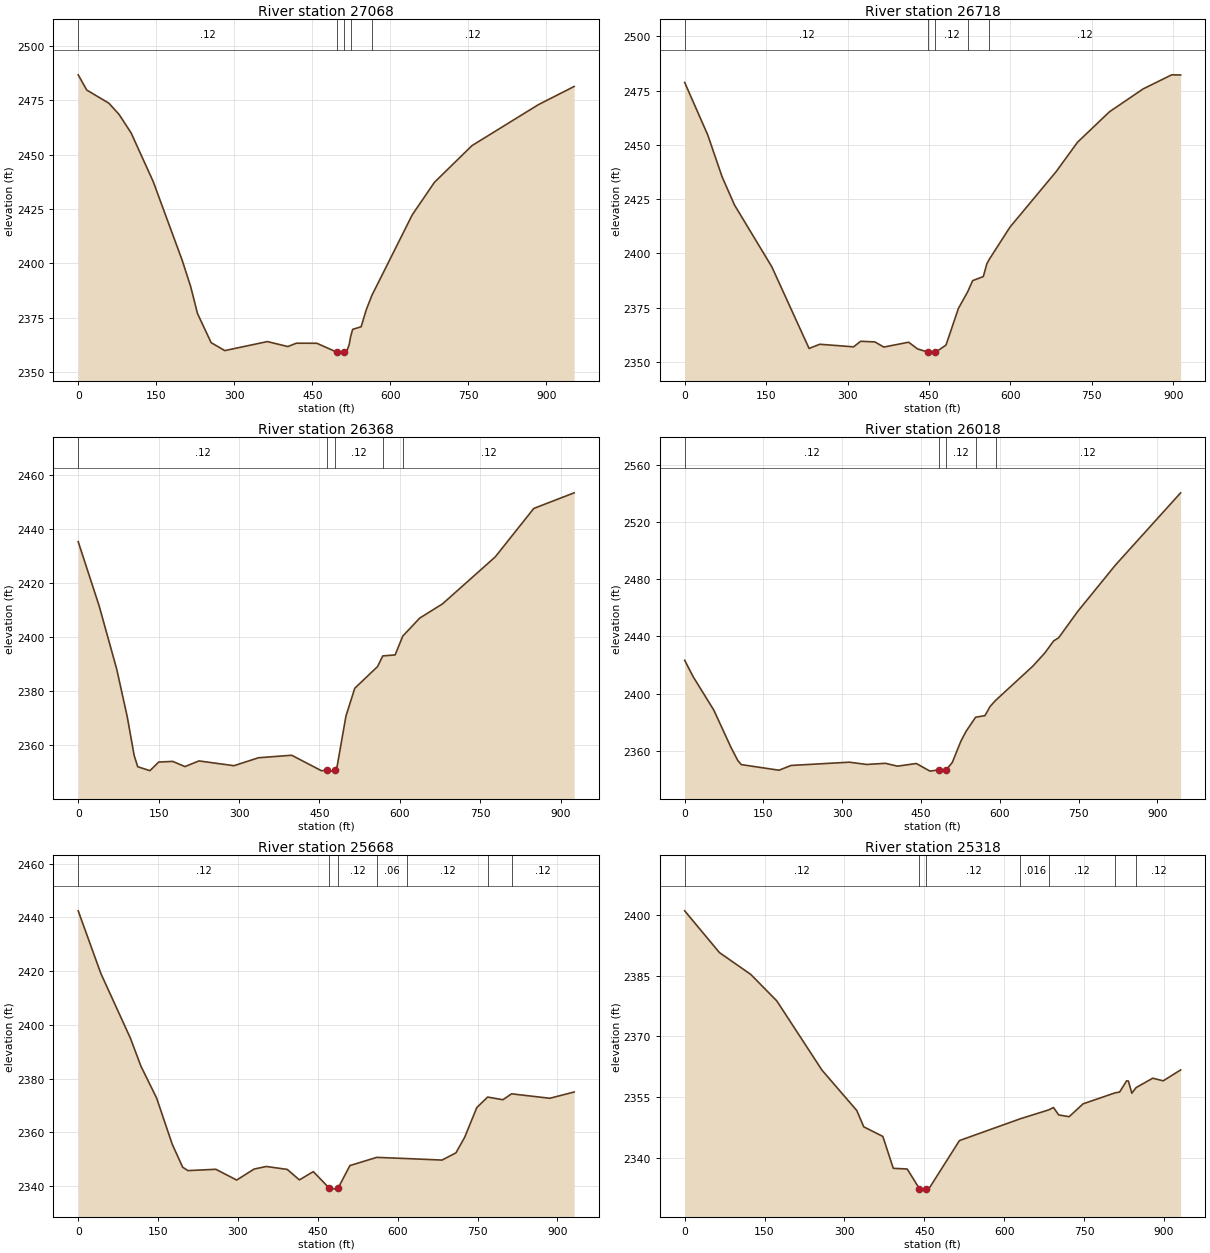
Type RM Length L Ch R = 1 ,27068   ,338,350,363.4
XS GIS Cut Line= 3
     2147314.201      245247.906     2147657.156      245622.321
     2147939.758      245966.672
#Sta/Elev= 30
       0 2486.79    16.4 2479.79      59 2473.72    78.6 2468.54   101.6 2460.08
   144.1 2437.68   199.8 2401.44   216.2 2389.27   229.3 2376.88   255.5 2363.48
   281.7 2359.83   363.6 2363.98   402.9 2361.69   419.3 2363.23   458.6  2363.2
   497.9 2359.02   504.5 2358.66     511 2358.97   517.6 2360.44   520.8 2362.61
   523.62366.233   527.4 2369.59   543.8 2370.81   553.6  2378.6  564.512385.272
     642 2422.32   684.6 2437.28   756.7 2454.18   884.4 2473.05   953.2 2481.42
#Mann= 5 ,-1 , 0
       0     .12       0   497.9    .045       0     511     .12       0
   523.6    .016       0  564.51     .12       0
Bank Sta=497.9,511
XS Rating Curve= 0 ,0
Exp/Cntr=0.3,0.1

Type RM Length L Ch R = 1 ,26718   ,341.8,350,352.9
XS GIS Cut Line= 3
       2147222.6      245287.473     2147331.185      245732.875
     2147371.573      246186.182
#Sta/Elev= 30
       0 2478.75    42.6 2454.49    68.8 2435.35    91.7  2422.3   160.5 2393.78
   229.2 2356.12   248.9 2358.06   311.1 2356.87   324.2 2359.43   350.4 2359.14
   366.8 2356.77   412.6    2359     429  2355.9   448.6 2354.41   455.2 2353.97
   461.7 2354.28   481.4 2357.69   504.3 2374.61  521.252382.202   530.5 2387.39
   550.1 2389.26   556.7 2395.19     5612397.163   599.2 2412.04   684.4 2437.66
   723.6 2451.17   782.6 2465.24   844.8 2475.81   897.2 2482.26   913.6 2482.18
#Mann= 5 ,-1 , 0
       0     .12       0   448.6    .045       0   461.7     .12       0
  521.25    .016       0     561     .12       0
Bank Sta=448.6,461.7
XS Rating Curve= 0 ,0
Exp/Cntr=0.3,0.1

Type RM Length L Ch R = 1 ,26368   ,338.3,350,361
XS GIS Cut Line= 3
     2147040.005      245313.384     2146986.956      245783.622
     2146963.209      246234.782
#Sta/Elev= 30
       0 2435.32    39.2 2411.45    71.8 2388.14    91.4 2370.55   104.4 2356.13
     111 2351.98   133.8 2350.52   150.1 2353.71   176.2 2353.96   199.1 2352.03
   225.2 2354.13   290.5 2352.36   336.2  2355.3   398.2 2356.23   453.6  2350.5
   463.4 2350.69   473.2 2350.35  478.442350.697     483 2352.22   499.4 2370.76
   515.8 2381.04   558.3 2389.07  568.042393.028   591.1 2393.39  605.382400.368
   636.9 2407.02   679.5  2412.3   777.7 2429.66   849.7 2447.64     925 2453.42
#Mann= 5 ,-1 , 0
       0     .12       0   463.4    .045       0  478.44     .12       0
  568.04    .016       0  605.38     .12       0
Bank Sta=463.4,478.44
XS Rating Curve= 0 ,0
Exp/Cntr=0.3,0.1

Type RM Length L Ch R = 1 ,26018   ,338.5,350,363.2
XS GIS Cut Line= 3
     2146944.529      245280.962     2146655.736      245684.707
     2146423.393      246067.392
#Sta/Elev= 30
       0 2423.28    16.3 2411.67    55.5 2388.37    88.2 2362.24   101.2 2353.07
   107.8 2350.24   179.6  2346.3   202.5 2349.64   313.5 2351.93   346.2 2350.34
   382.1 2351.14     405 2349.15   440.9 2351.02     467 2345.67   483.3 2346.53
  497.892346.531   509.5  2351.8   525.8 2366.65   535.6  2373.5  553.872383.423
   571.6 2384.51   581.4 2390.93  591.712395.121   663.1 2419.29   685.9 2428.52
   702.3 2436.81   712.1 2439.12     748 2457.37   819.9  2489.9   944.1 2540.51
#Mann= 5 ,-1 , 0
       0     .12       0   483.3    .045       0  497.89     .12       0
  553.87    .016       0  591.71     .12       0
Bank Sta=483.3,497.89
XS Rating Curve= 0 ,0
Exp/Cntr=0.3,0.1

Type RM Length L Ch R = 1 ,25668   ,363.4,350,339.2
XS GIS Cut Line= 3
     2146882.333      245202.822     2146448.941      245410.984
     2146038.576      245596.918
#Sta/Elev= 30
       0 2442.46    42.5 2419.14    98.1 2395.01   117.7 2384.65   147.2 2372.76
   176.6 2355.53   196.2 2346.98     206 2345.73   258.4 2346.22   297.6 2342.21
   330.3  2346.3   353.2 2347.27   392.5 2346.17   415.4 2342.27   441.5 2345.35
     471 2339.29   484.1 2338.83   488.3 2339.31   510.2  2347.6  560.522350.653
  618.032350.201   683.2 2349.65   709.3 2352.34   725.6 2358.08   748.5 2369.21
  768.822373.115   797.5 2372.12  813.86 2374.32   885.6 2372.66   931.3    2375
#Mann= 7 ,-1 , 0
       0     .12       0     471    .045       0   488.3     .12       0
  560.52     .06       0  618.03     .12       0  768.82    .016       0
  813.86     .12       0
Bank Sta=471,488.3
XS Rating Curve= 0 ,0
Exp/Cntr=0.3,0.1

Type RM Length L Ch R = 1 ,25318   ,344.9,350,350.5
XS GIS Cut Line= 3
     2146497.113       244740.53     2146276.269      245133.139
     2145974.541       245507.39
#Sta/Elev= 30
       0 2401.08    65.3 2390.75     124 2385.36     173  2378.8   257.9 2361.66
   323.2 2351.68   336.2 2347.66   372.1 2345.27   391.7 2337.39   417.8 2337.22
   440.7 2332.38   443.9 2332.24   453.7 2332.37   460.3 2332.69   515.9 2344.25
  630.532349.658  683.71 2351.85   692.5 2352.43   702.3 2350.59   721.9 2350.16
   748.1 2353.34  808.042356.049   816.7 2356.26   829.8 2359.03   833.1 2358.98
   839.6 2355.97  847.74 2357.37   878.9 2359.68   898.5 2359.03   931.2 2361.72
#Mann= 7 ,-1 , 0
       0     .12       0   440.7    .045       0   453.7     .12       0
  630.53    .016       0  683.71     .12       0  808.04    .016       0
  847.74     .12       0
Bank Sta=440.7,453.7
XS Rating Curve= 0 ,0
Exp/Cntr=0.3,0.1

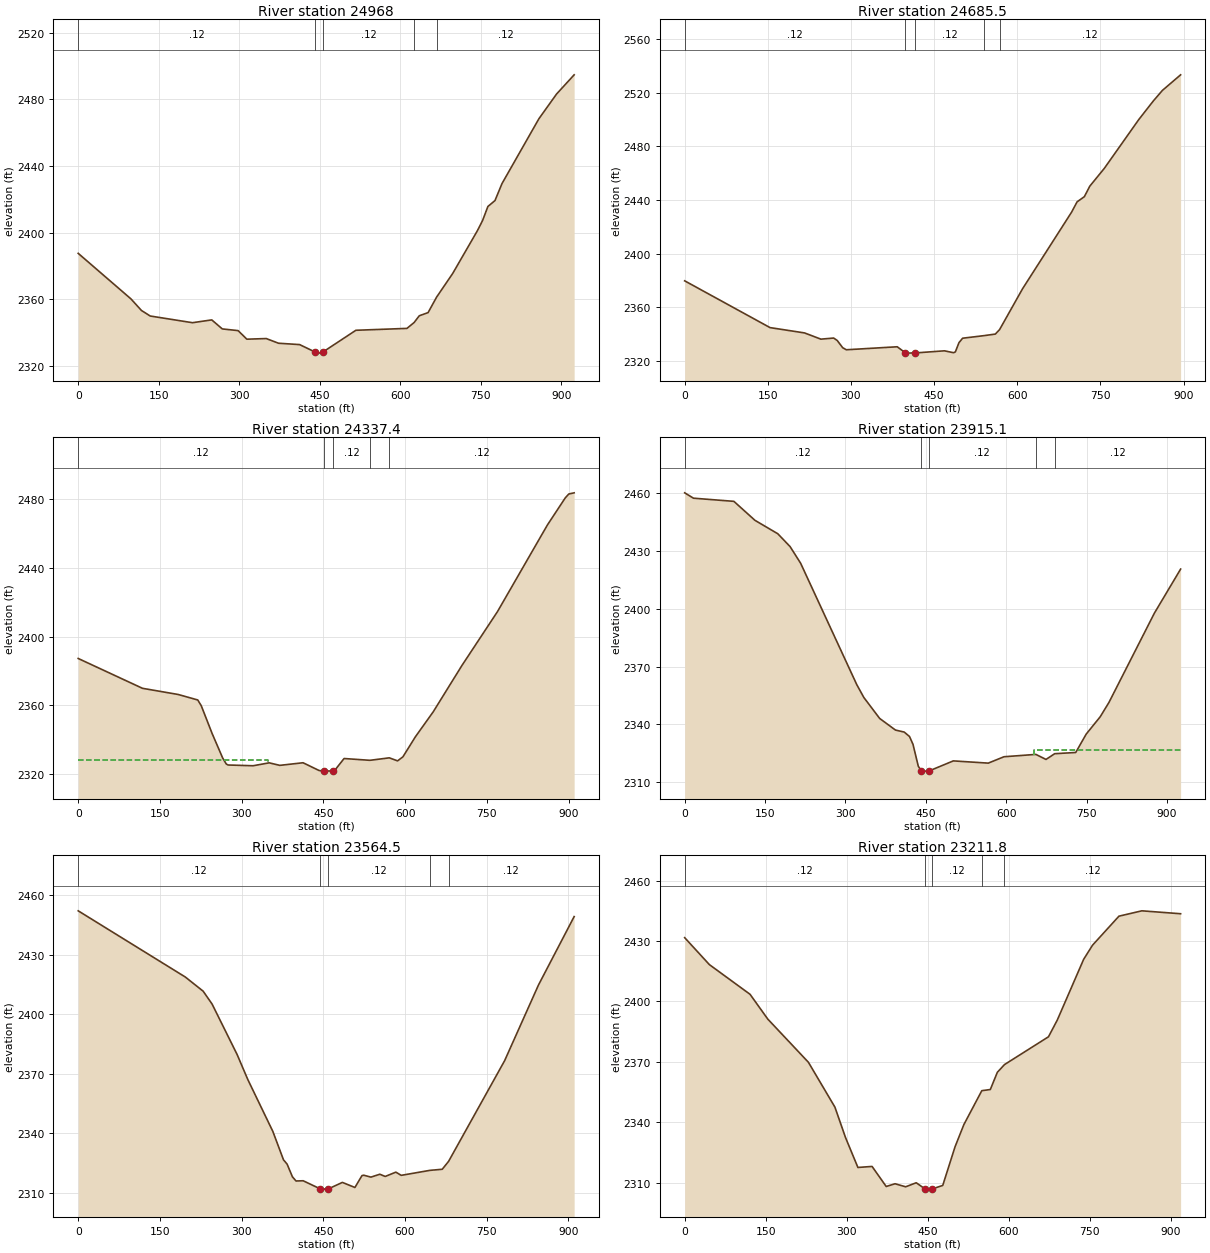
Type RM Length L Ch R = 1 ,24968   ,286.2,282.5,276.9
XS GIS Cut Line= 3
     2146293.004      244594.917     2146006.423      244944.117
     2145698.536      245302.088
#Sta/Elev= 30
       0 2387.59    98.2 2360.26   117.8 2353.29   134.2 2349.96   212.8 2345.95
   248.8 2347.63   268.4 2342.22   297.9 2341.19   314.2 2336.05   350.3 2336.43
   373.2 2333.62   412.5  2332.8   441.9 2328.25   451.7 2327.68  455.682328.308
   517.3  2341.4   612.4 2342.53  625.792346.068   635.4 2350.11   651.8 2352.01
  667.732361.344   697.7 2375.54   743.6 2401.15   753.4 2407.36   763.2 2415.73
   776.4 2419.28   789.5 2429.49   858.3 2468.44   891.1 2483.24   923.9 2494.78
#Mann= 5 ,-1 , 0
       0     .12       0   441.9    .045       0  455.68     .12       0
  625.79    .016       0  667.73     .12       0
Bank Sta=441.9,455.68
XS Rating Curve= 0 ,0
Exp/Cntr=0.3,0.1

Type RM Length L Ch R = 1 ,24685.5 ,345.8,348.1,349.4
XS GIS Cut Line= 2
     2145988.284      244417.304     2145559.518      245202.647
#Sta/Elev= 30
       0 2379.62     154 2344.67   216.3 2340.69   245.8 2336.04   268.8 2336.87
   275.3 2335.02   285.1 2329.64   291.7 2328.11   383.5 2330.35  398.342325.776
   399.7  2325.6   416.2 2325.75   468.7 2327.32   485.1 2325.92   488.4 2326.52
   494.9 2333.43   501.5 2336.74  540.392338.678   560.5 2339.83  568.242343.218
   609.6 2373.68   698.1 2430.94     708 2438.63   721.1 2442.49   730.9 2450.32
   757.1 2463.63   819.4 2500.16   845.6 2514.03     862 2521.92   894.8 2533.54
#Mann= 5 ,-1 , 0
       0     .12       0  398.34    .045       0   416.2     .12       0
  540.39    .016       0  568.24     .12       0
Bank Sta=398.34,416.2
XS Rating Curve= 0 ,0
Exp/Cntr=0.3,0.1

Type RM Length L Ch R = 1 ,24337.4 ,427.6,422.3,414.7
XS GIS Cut Line= 3
     2145738.613      244250.597     2145484.128      244627.967
     2145238.873      245011.176
#Sta/Elev= 30
       0 2387.31   117.9 2369.93   183.4 2366.33   219.4 2363.13   225.9 2359.72
   245.6  2343.7   265.2 2329.26   271.8 2325.78   275.1 2325.24   320.9  2324.8
   350.4  2326.5     370 2325.03   412.6 2326.55   442.1 2322.02   451.9 2321.67
   467.4 2321.82   471.5 2322.43   487.9 2329.02  535.322327.967  570.892329.413
   586.1 2327.64   595.9 2330.02   618.8 2341.69   651.6 2356.28   703.9 2383.09
   769.4 2414.61     861 2465.08   893.8 2480.88   900.3 2483.15   910.1 2483.83
#Mann= 5 ,-1 , 0
       0     .12       0   451.9    .045       0   467.4     .12       0
  535.32    .016       0  570.89     .12       0
#XS Ineff= 2 , 0
          347.47 2328.32
Permanent Ineff=
       F       F
Bank Sta=451.9,467.4
XS Rating Curve= 0 ,0
Exp/Cntr=0.3,0.1

Type RM Length L Ch R = 1 ,23915.1 ,355.6,350.6,343.7
XS GIS Cut Line= 3
      2145293.26       243966.55     2145150.462      244399.114
     2144985.323      244838.955
#Sta/Elev= 30
       0 2460.18    16.4  2457.4    91.8 2455.76   131.1 2445.92   173.7 2438.96
   196.6 2432.31   216.3 2423.68   321.2 2360.61   334.3 2354.01   363.8 2343.14
   393.3 2337.11   409.6 2336.07   419.5 2333.77     426  2329.7   435.9 2318.31
  441.632315.983   445.7 2315.81   455.5 2315.84   501.2 2321.12   566.4 2319.96
   595.8 2323.27  655.272324.484   674.1 2321.88  690.42 2324.85   729.6 2325.48
   749.2 2335.04   775.3 2344.01   791.6 2351.45   876.4 2397.78   925.3 2420.61
#Mann= 5 ,-1 , 0
       0     .12       0  441.63    .045       0   455.5     .12       0
  655.27    .016       0  690.42     .12       0
#XS Ineff= 2 , 0
                          652.44         2326.69
Permanent Ineff=
       F       F
Bank Sta=441.63,455.5
XS Rating Curve= 0 ,0
Exp/Cntr=0.3,0.1

Type RM Length L Ch R = 1 ,23564.5 ,340.8,352.7,366.1
XS GIS Cut Line= 3
     2144852.001      243893.172     2144808.711      244346.694
     2144774.377      244800.306
#Sta/Elev= 30
       0  2452.1   196.6 2418.72   229.4 2411.57   245.8 2405.08   291.7 2379.66
   311.4    2367   357.3 2340.87   376.9 2326.52   383.5 2324.37   393.3 2317.96
   399.9 2315.85     413 2315.97  443.992311.928   455.6 2311.75   458.9 2311.84
     485 2315.14     508 2312.58     521 2318.59   524.3 2318.76   537.4 2317.81
   553.8 2319.26   563.6 2318.14   583.2 2320.32     593  2318.7  645.812321.221
   668.3 2321.76  679.982325.746   782.9 2376.54     845 2414.68   910.5 2449.19
#Mann= 5 ,-1 , 0
       0     .12       0  443.99    .045       0   458.9     .12       0
  645.81    .016       0  679.98     .12       0
Bank Sta=443.99,458.9
XS Rating Curve= 0 ,0
Exp/Cntr=0.3,0.1

Type RM Length L Ch R = 1 ,23211.8 ,340.9,350.6,351.4
XS GIS Cut Line= 3
     2144759.911      243861.716     2144500.448      244243.461
     2144184.043      244572.994
#Sta/Elev= 30
       0  2431.7    45.8 2418.29   121.1 2403.54   153.9 2391.23   229.2 2369.74
   278.2 2347.48   297.9 2332.31   320.8 2317.48     347 2317.99   373.2 2308.02
   389.6 2309.38   409.2 2307.87   428.8 2309.88   445.2 2306.79   448.5 2306.71
   458.3  2306.8   477.9 2308.54   500.7 2327.77     517 2338.78  550.242355.647
     566 2356.22     579 2364.77  592.19  2368.6   673.7 2382.43     690 2390.73
   738.9 2420.97   755.3 2427.96   804.2 2442.38   846.6 2445.04   918.4 2443.59
#Mann= 5 ,-1 , 0
       0     .12       0   445.2    .045       0   458.3     .12       0
  550.24    .016       0  592.19     .12       0
Bank Sta=445.2,458.3
XS Rating Curve= 0 ,0
Exp/Cntr=0.3,0.1

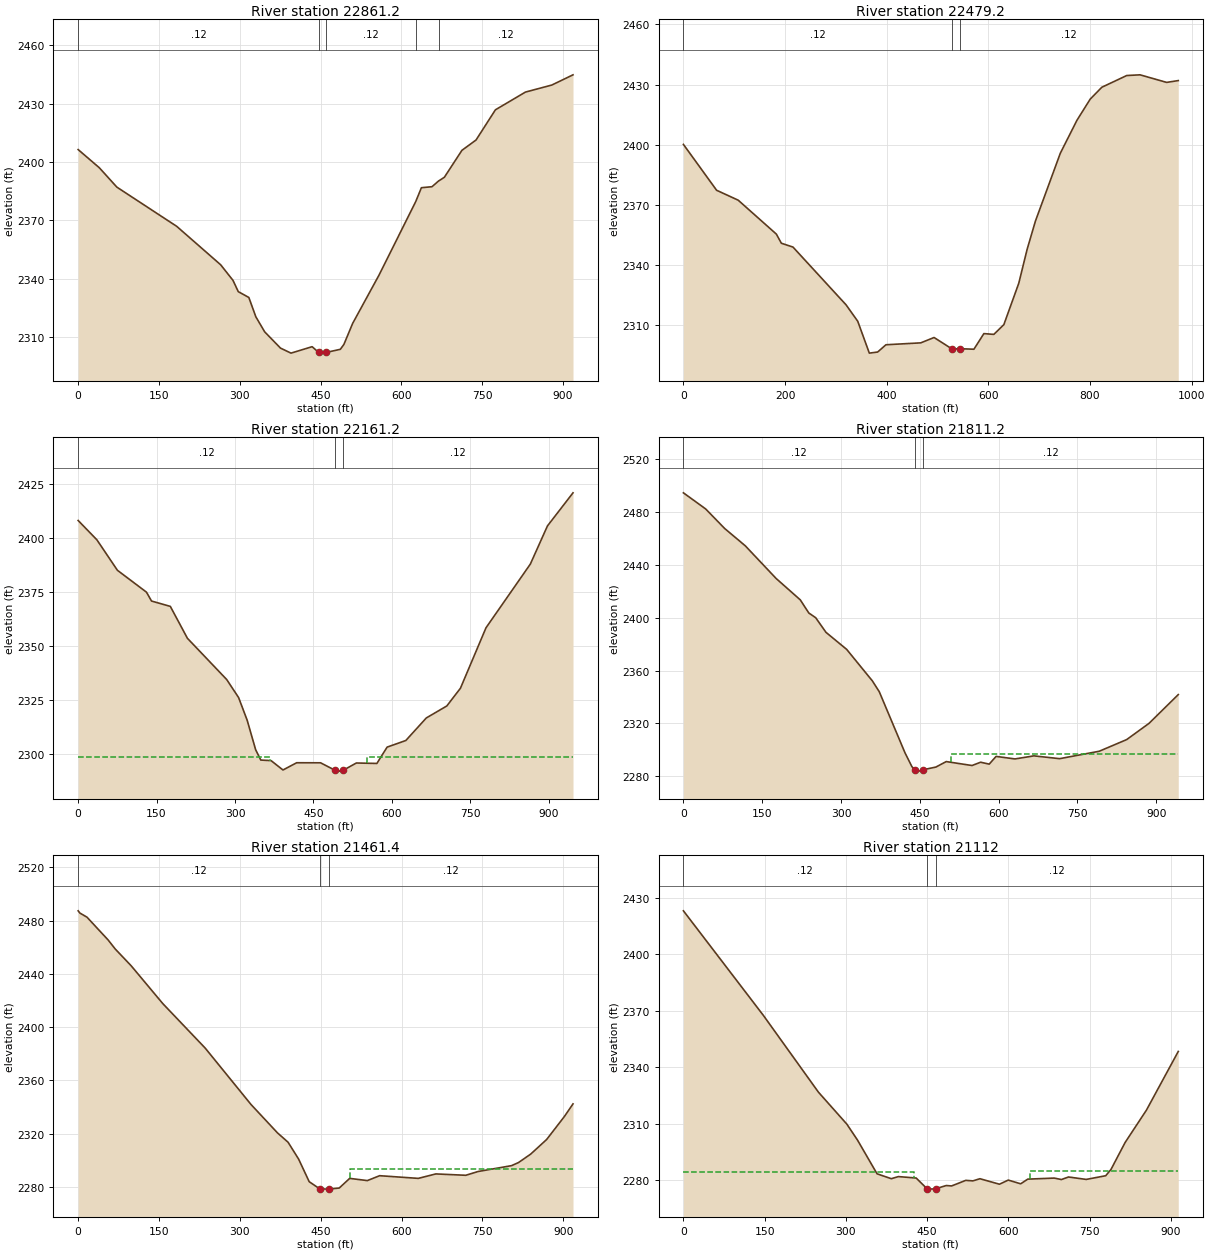
Type RM Length L Ch R = 1 ,22861.2 ,371.3,382,398
XS GIS Cut Line= 3
     2144650.411      243741.205     2144267.927      243985.647
     2143947.399       244321.91
#Sta/Elev= 30
       0 2406.38    39.2 2397.07    71.8  2387.1   182.9 2366.95   264.5  2347.2
   287.4 2339.18   297.2 2333.39   316.8  2330.4   329.8 2320.47   346.2 2312.74
   375.6 2304.37   395.1  2301.8   434.3 2305.11   446.4 2302.15   460.5 2302.16
   486.6 2303.76   493.2 2306.24   509.5 2317.07   558.6 2341.97  626.762379.774
   637.1 2386.78   656.8 2387.31  668.892390.219   679.7 2392.14   712.4 2406.02
   738.5 2411.29   774.5 2426.82   830.2 2435.92   879.2 2439.54   918.5 2444.79
#Mann= 5 ,-1 , 0
       0     .12       0   446.4    .045       0   460.5     .12       0
  626.76    .016       0  668.89     .12       0
Bank Sta=446.4,460.5
XS Rating Curve= 0 ,0
Exp/Cntr=0.3,0.1

Type RM Length L Ch R = 1 ,22479.2 ,307.3,318,332.6
XS GIS Cut Line= 3
     2144611.315      243624.324     2144081.715      243678.928
     2143642.093      243716.868
#Sta/Elev= 30
       0 2400.17    65.3 2377.31   107.8 2372.37   182.9 2355.45   192.7 2350.92
   215.6    2349   320.1  2320.2     343 2312.03   365.8 2296.15   382.2  2296.7
   398.5 2300.32   467.1 2301.27   493.2 2303.94   528.5 2298.22   543.5 2298.36
   571.6 2298.09   591.2 2305.88   610.8 2305.49   630.5 2310.35   659.9    2331
   676.2 2347.78   692.6 2361.93   741.6 2395.76   774.3 2412.18   800.4 2422.72
   823.3 2428.65   872.3 2434.49   898.5 2434.84   950.8 2431.07   973.7 2431.97
#Mann= 3 ,-1 , 0
       0     .12       0   528.5    .045       0   543.5     .12       0
Bank Sta=528.5,543.5
XS Rating Curve= 0 ,0
Exp/Cntr=0.3,0.1

Type RM Length L Ch R = 1 ,22161.2 ,351.9,350,349
XS GIS Cut Line= 3
     2144627.337      243561.344     2144162.056      243379.401
     2143783.845      243141.103
#Sta/Elev= 30
       0 2408.24    35.9 2399.26    75.1 2385.15   130.6 2375.02   140.4 2370.88
   176.3 2368.41     209 2353.62   284.1  2334.5   306.9 2326.14   323.3 2315.62
   339.6 2301.89   349.4 2297.14     369 2296.89   391.8 2292.54     418  2295.9
   463.7 2295.87   492.1 2292.33   499.6 2292.01   507.1 2292.43   532.2 2295.78
   571.4 2295.57     591 2303.14   626.8 2306.21     666 2316.67   705.2 2322.23
   731.3 2330.46   780.2  2358.5     865 2388.03   897.7 2405.71   946.6 2421.07
#Mann= 3 ,-1 , 0
       0     .12       0   492.1    .045       0   507.1     .12       0
#XS Ineff= 2 , 0
          366.97  2298.5  553.03         2298.41
Permanent Ineff=
       F       F
Bank Sta=492.1,507.1
XS Rating Curve= 0 ,0
Exp/Cntr=0.3,0.1

Type RM Length L Ch R = 1 ,21811.2 ,350,349.8,342.1
XS GIS Cut Line= 3
     2144822.357      243266.046      2144393.65      243135.999
     2143973.691      242875.931
#Sta/Elev= 30
       0 2494.74    42.5 2482.47    78.5 2467.71   117.7 2454.61   176.6 2429.78
   222.4 2413.65   238.7 2403.66   251.8 2400.09   271.4    2389   310.7 2376.12
   359.7  2352.2   372.8 2344.03   421.8 2297.69   434.9 2287.25   440.5  2284.8
     448 2283.83   455.5  2284.8   480.7 2286.93   500.3 2291.06   549.4 2288.08
   565.8 2290.58   582.1 2289.13   595.2 2294.99   631.2 2293.07   667.2  2295.4
   716.2 2293.27   791.5 2298.89   843.8 2307.73   886.4 2320.06     942 2341.83
#Mann= 3 ,-1 , 0
       0     .12       0   440.5    .045       0   455.5     .12       0
#XS Ineff= 2 , 0
                          508.77         2296.88
Permanent Ineff=
       F       F
Bank Sta=440.5,455.5
XS Rating Curve= 0 ,0
Exp/Cntr=0.3,0.1

Type RM Length L Ch R = 1 ,21461.4 ,349,349.4,347.7
XS GIS Cut Line= 3
     2144903.693       242917.19     2144455.741      242793.894
     2144014.657       242689.49
#Sta/Elev= 30
       0 2487.29     3.3  2485.6    16.4 2482.52    55.6 2465.42    68.7 2458.67
    98.2 2446.11     157 2417.66   235.6 2384.28   320.6 2341.96   369.7 2320.64
   389.4 2313.59     409 2300.91   428.6 2283.97   448.2  2278.6   461.3 2278.41
   464.6 2278.46   484.2 2279.22   503.7 2286.48   536.4 2284.81   559.2 2288.49
   630.9 2286.48   663.5 2289.82     719  2288.8   741.8 2291.63   803.8 2296.02
   816.8 2298.35   839.6 2304.76     869 2315.66   901.6 2332.74   917.9 2342.37
#Mann= 3 ,-1 , 0
       0     .12       0   448.2    .045       0   464.6     .12       0
#XS Ineff= 2 , 0
                          504.64          2293.5
Permanent Ineff=
       F       F
Bank Sta=448.2,464.6
XS Rating Curve= 0 ,0
Exp/Cntr=0.3,0.1

Type RM Length L Ch R = 1 ,21112   ,289.8,298.7,308.7
XS GIS Cut Line= 3
     2145028.627      242594.327     2144585.757      242473.337
     2144138.998      242391.038
#Sta/Elev= 30
       0 2423.08   147.6  2367.5   249.2 2326.72   301.7 2309.71   321.4 2301.22
   357.4 2283.33   383.7 2280.74   396.8 2281.85   429.6 2281.09   449.3 2275.51
   455.8 2275.19   465.6 2275.39   485.2  2277.1     495 2276.88   521.2 2279.85
   534.3 2279.57   547.3 2280.72   583.3  2277.8   599.6 2279.99   622.5 2278.02
   635.6  2280.5   684.6 2281.06   697.7 2280.28   710.8 2281.64   743.4 2280.35
   779.4  2282.3   789.2 2285.64   815.3 2299.98   854.6 2317.15   913.4 2348.35
#Mann= 3 ,-1 , 0
       0     .12       0   449.3    .045       0   465.6     .12       0
#XS Ineff= 2 , 0
          426.21 2284.32  639.83         2284.93
Permanent Ineff=
       F       F
Bank Sta=449.3,465.6
XS Rating Curve= 0 ,0
Exp/Cntr=0.3,0.1

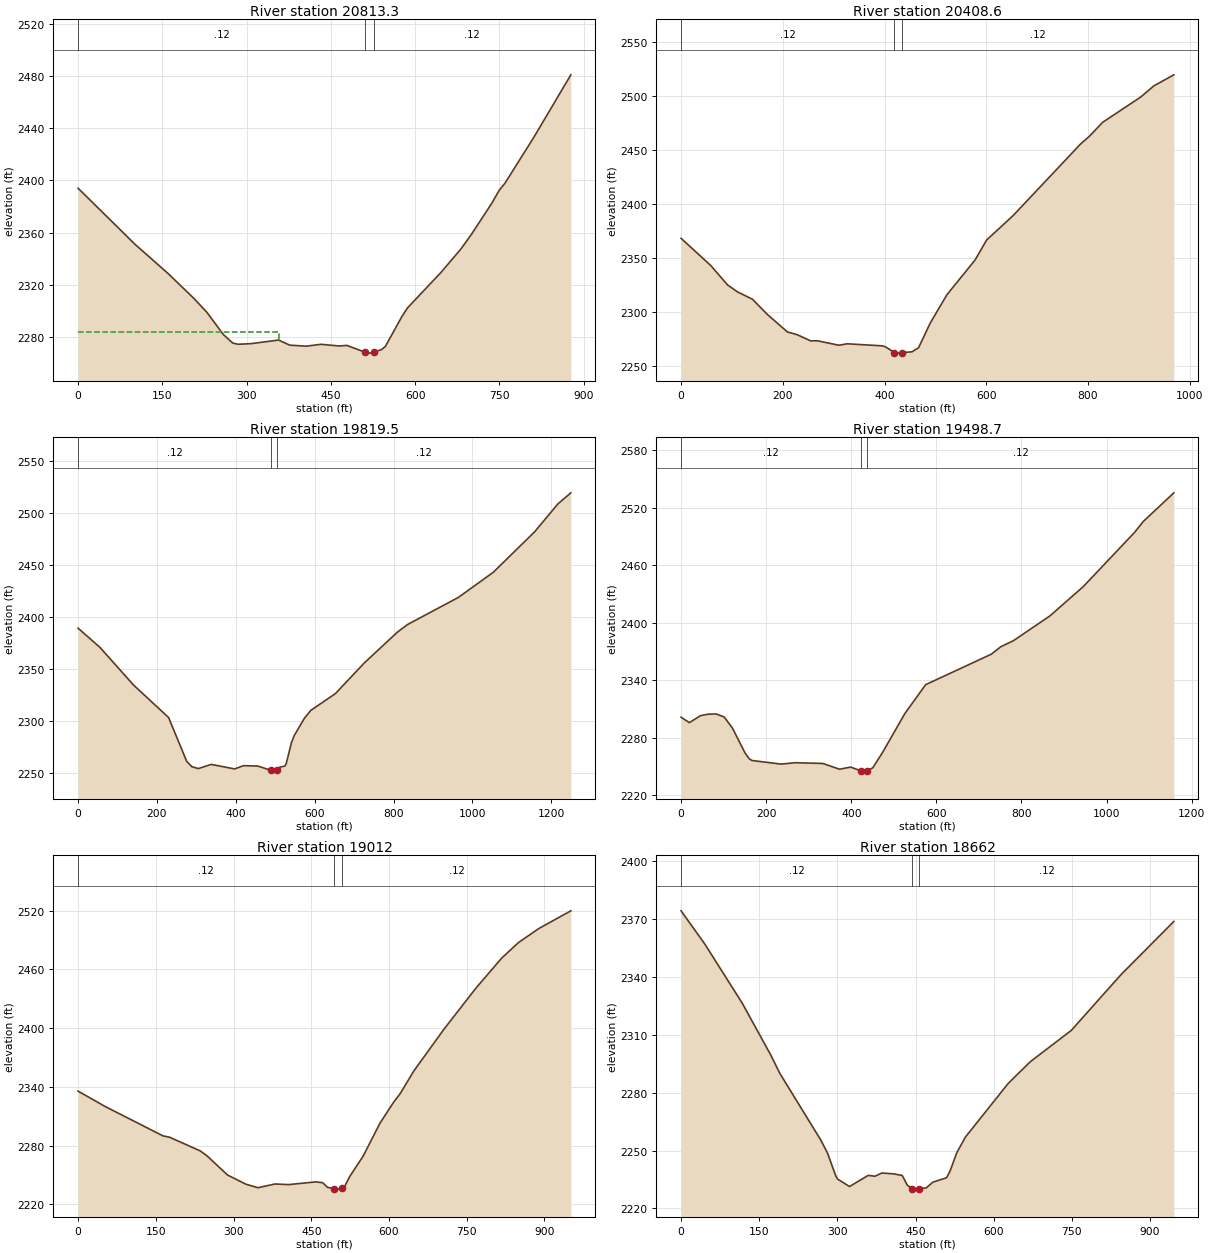
Type RM Length L Ch R = 1 ,20813.3 ,391.7,404.8,417.6
XS GIS Cut Line= 3
     2145069.499      242496.605      2144579.48      242129.091
     2144505.102      241875.332
#Sta/Elev= 30
       0 2394.01   101.5 2350.92   160.5 2328.46   206.4 2309.38   229.3  2298.8
   258.8 2281.68   275.1 2275.29     285 2274.31   307.9 2274.79     357 2277.55
   376.7 2273.62   406.2 2272.83   432.4 2274.28   465.1 2272.97   478.2 2273.46
     511  2268.2   520.8 2267.51  526.152268.137   540.5 2270.34     547 2272.72
   576.5 2295.67   586.3 2302.19   645.2 2329.09   681.1 2347.24   700.7 2358.99
   736.6 2382.64   749.6 2392.47   759.4 2397.57   811.7 2433.43     877 2480.96
#Mann= 3 ,-1 , 0
       0     .12       0     511    .045       0  526.15     .12       0
#XS Ineff= 2 , 0
           358.1 2283.78
Permanent Ineff=
       F       F
Bank Sta=511,526.15
XS Rating Curve= 0 ,0
Exp/Cntr=0.3,0.1

Type RM Length L Ch R = 1 ,20408.6 ,620.6,589.1,556.7
XS GIS Cut Line= 3
     2145170.128       242428.79     2144988.558      241938.772
     2144564.167      241800.954
#Sta/Elev= 30
       0 2368.41    58.8 2343.04    91.4 2325.28     111 2318.82   140.4 2312.04
   169.8 2297.93     209 2281.82   228.6 2279.19   254.8 2273.54   267.8 2273.63
   310.3 2269.49   326.6 2270.84   395.2 2268.94   401.7 2268.12  419.582262.711
   424.6  2262.2   434.4 2262.64     454 2263.41     467 2267.23   489.9 2290.01
   522.6 2316.13     578 2348.29   600.7  2366.8   652.9 2389.43   786.4 2456.06
   802.7 2462.67   828.7  2475.6   903.6    2499   929.7 2509.41   968.8 2519.57
#Mann= 3 ,-1 , 0
       0     .12       0  419.58    .045       0   434.4     .12       0
Bank Sta=419.58,434.4
XS Rating Curve= 0 ,0
Exp/Cntr=0.3,0.1

Type RM Length L Ch R = 1 ,19819.5 ,344.1,320.8,296.5
XS GIS Cut Line= 2
     2145808.902      241551.569     2144581.668      241785.641
#Sta/Elev= 30
       0 2389.16    55.8 2370.54     141 2334.22   229.5 2303.11   275.4 2260.89
   288.6 2255.68     305 2253.88   337.8  2257.9   396.8 2253.55   419.7 2256.68
   455.8 2256.32   488.6 2252.24   501.7 2251.42     505 2252.24   511.6  2255.3
   524.7 2256.31   527.9 2258.86   541.1 2278.86   547.6 2285.35   573.8 2302.28
   590.2 2309.97   652.6 2326.12   724.7 2355.26     810 2385.43   836.2 2392.82
   964.1 2418.73  1052.6 2442.94  1157.5 2481.93  1216.6 2508.85  1249.4 2519.53
#Mann= 3 ,-1 , 0
       0     .12       0   488.6    .045       0     505     .12       0
Bank Sta=488.6,505
XS Rating Curve= 0 ,0
Exp/Cntr=0.3,0.1

Type RM Length L Ch R = 1 ,19498.7 ,475.7,486.6,497.1
XS GIS Cut Line= 3
     2145233.568      241074.676     2145043.248      241617.197
     2144472.288      241735.326
#Sta/Elev= 30
       0 2301.27    19.6 2295.65    45.7 2302.88    62.1 2304.35    81.7 2304.74
   101.3 2301.56   120.9 2289.82   150.3    2264   160.1 2257.94   166.6 2256.09
   235.2 2252.32   267.9 2253.76   333.2 2252.99   372.4    2247   398.5 2249.19
   423.1 2245.25   427.9 2244.99   438.1 2245.28   450.8 2248.57   473.7  2264.6
   525.9 2305.11   574.9 2335.29   728.9 2367.03   751.8 2374.96   781.3 2381.23
   866.5 2406.95   945.1 2437.59  1066.3 2494.51  1085.9  2505.5    1158 2535.54
#Mann= 3 ,-1 , 0
       0     .12       0   423.1    .045       0   438.1     .12       0
Bank Sta=423.1,438.1
XS Rating Curve= 0 ,0
Exp/Cntr=0.3,0.1

Type RM Length L Ch R = 1 ,19012   ,342,350,350.3
XS GIS Cut Line= 3
     2145002.143      240954.884     2144639.584       241305.72
     2144314.055        241611.2
#Sta/Elev= 30
       0 2335.75    52.4    2320   163.8 2290.05   176.9 2288.58   235.9 2274.64
     249 2269.56   288.3  2250.1   324.3 2240.58   347.3 2237.08     380 2240.88
   406.2 2240.25   458.6 2243.02   471.8 2242.24   481.6 2237.38   494.7 2236.25
   504.5 2235.63  509.152236.313   514.3 2238.17   524.1 2248.43   550.1  2269.3
   582.7 2303.09   608.8  2324.3   621.8 2333.34   647.9 2356.29   706.5 2399.31
   768.4 2441.34   817.3 2471.53   849.9 2487.49     889 2501.79   950.9  2519.9
#Mann= 3 ,-1 , 0
       0     .12       0   494.7    .045       0  509.15     .12       0
Bank Sta=494.7,509.15
XS Rating Curve= 0 ,0
Exp/Cntr=0.3,0.1

Type RM Length L Ch R = 1 ,18662   ,373.9,350,340.5
XS GIS Cut Line= 3
       2144921.4      240800.162     2144513.308      240983.386
     2144137.215      241310.471
#Sta/Elev= 30
       0 2374.11    45.7 2356.88   117.6 2326.22   173.1 2298.98   189.4 2290.02
   267.8 2255.59   280.8 2248.87   297.1 2236.76   300.4 2235.22   323.3 2231.35
   359.2 2237.11   372.2 2236.67   385.3 2238.35   408.2  2237.9   424.5 2237.07
   434.3 2232.04  442.742230.212   447.3    2230   457.2 2230.19   470.3 2230.62
   483.4  2233.6   509.6  2235.9   516.2  2239.3   529.3 2248.92   545.7 2256.92
   627.7 2284.67   670.3 2295.97     749  2312.2   844.1 2340.97   945.8 2368.61
#Mann= 3 ,-1 , 0
       0     .12       0  442.74    .045       0   457.2     .12       0
Bank Sta=442.74,457.2
XS Rating Curve= 0 ,0
Exp/Cntr=0.3,0.1

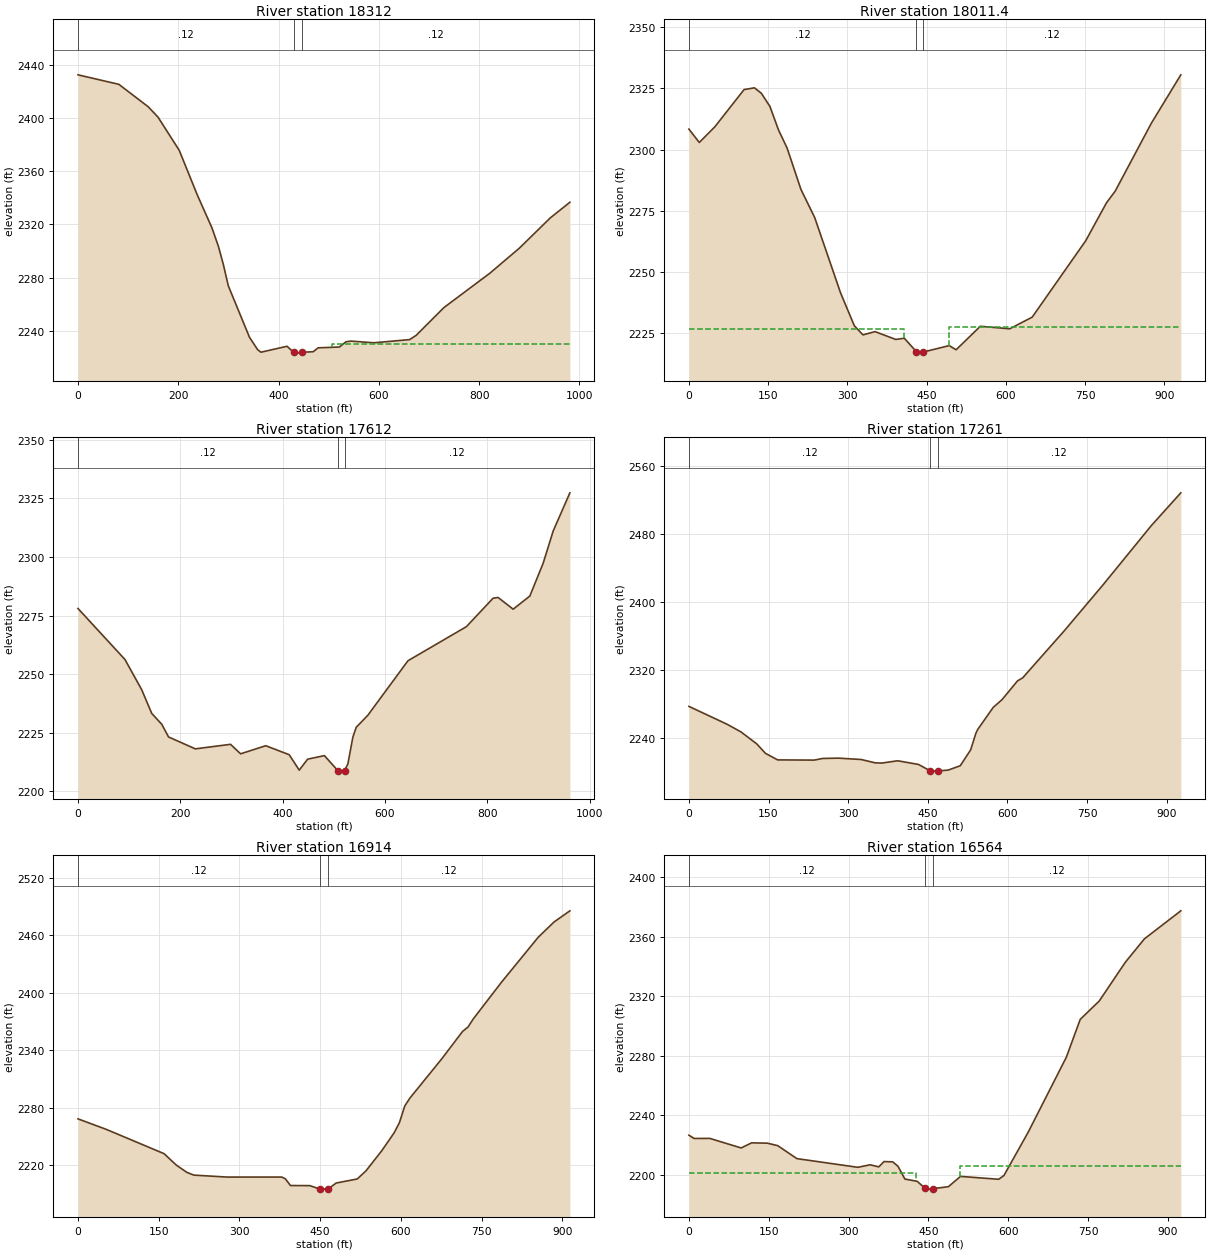
Type RM Length L Ch R = 1 ,18312   ,307.8,300.6,286.5
XS GIS Cut Line= 3
     2144325.662      240316.555     2144284.823      240754.517
     2144068.364      241250.739
#Sta/Elev= 30
       0 2432.29    81.5 2425.15   140.1  2408.3   159.6 2400.55     202 2375.59
   237.8 2342.31   267.2 2317.41   280.2 2303.44     290 2289.83   299.8 2273.96
   342.1 2235.32   358.4    2226   364.9 2224.13     417 2228.58   430.1 2224.01
   436.6 2223.44   446.4 2224.05   469.2  2224.5     479 2227.42   521.4 2228.02
   534.4 2231.93   544.2 2232.48   589.9  2231.2   661.6 2233.59   674.7 2236.84
   730.1 2257.68   821.4 2283.37   880.1 2302.11   942.1 2324.92   981.2 2336.67
#Mann= 3 ,-1 , 0
       0     .12       0   430.1    .045       0   446.4     .12       0
#XS Ineff= 2 , 0
                          506.23         2230.26
Permanent Ineff=
       F       F
Bank Sta=430.1,446.4
XS Rating Curve= 0 ,0
Exp/Cntr=0.3,0.1

Type RM Length L Ch R = 1 ,18011.4 ,387.9,399.4,405.4
XS GIS Cut Line= 3
     2143901.828      240321.433     2144007.064      240765.806
     2144025.254      241239.776
#Sta/Elev= 30
       0 2308.33    19.6 2302.89    48.9 2309.24   104.4 2324.46     124 2325.17
     137 2322.97   153.3 2317.58   169.6 2307.97   185.9 2300.57     212 2283.75
   238.1 2272.25     287 2241.56   313.1 2228.13   329.4 2224.43   352.3 2225.76
   391.4 2222.57   407.7 2223.05   430.6 2217.56   437.1 2216.99   443.6 2217.43
   492.6 2220.06   505.7 2218.36   551.5 2227.94   607.1 2226.91   649.7 2231.66
   751.1 2262.85   790.3 2278.28   806.7 2283.01   875.4  2310.8     931 2330.47
#Mann= 3 ,-1 , 0
       0     .12       0   430.6    .045       0   443.6     .12       0
#XS Ineff= 2 , 0
          407.64 2226.96  492.26         2227.67
Permanent Ineff=
       F       F
Bank Sta=430.6,443.6
XS Rating Curve= 0 ,0
Exp/Cntr=0.3,0.1

Type RM Length L Ch R = 1 ,17612   ,339.9,351,367.5
XS GIS Cut Line= 3
     2143753.691      240330.581     2143619.141      240830.397
     2143574.349      241271.937
#Sta/Elev= 30
       0 2278.02    91.7 2256.26   124.5 2243.34   144.1 2233.22   163.8 2228.55
   176.9 2223.17   229.3 2218.08   298.1 2220.02   317.8 2215.96   366.9 2219.42
   412.8 2215.58   432.4 2208.99   448.8 2213.68   481.6 2215.19   507.8 2208.79
   514.3 2208.57   520.9 2208.77   527.4 2211.62   537.2 2223.07   543.7 2227.27
   566.6 2232.46   644.9 2255.71   759.1 2270.26   811.3 2282.42   821.1 2282.73
   850.5 2277.73   883.1 2283.34   909.2 2297.39   928.8 2311.16   961.4 2327.42
#Mann= 3 ,-1 , 0
       0     .12       0   507.8    .045       0   520.9     .12       0
Bank Sta=507.8,520.9
XS Rating Curve= 0 ,0
Exp/Cntr=0.3,0.1

Type RM Length L Ch R = 1 ,17261   ,345.6,347.1,345.7
XS GIS Cut Line= 3
     2143671.134      240276.196     2143345.441      240622.087
     2142987.609      240897.344
#Sta/Elev= 30
       0 2277.28    72.1 2256.25    98.3  2247.2   127.8 2233.23   144.2 2222.09
   167.1 2214.43   235.9 2214.18   252.3 2216.14   281.8 2216.47   324.4  2214.9
   350.6    2211   363.7 2210.72   393.2  2213.4   432.5 2209.08  454.512201.542
   458.7 2201.23   468.5 2201.41   488.2 2202.42   511.1 2207.55   530.7 2226.24
   540.5  2245.6   543.8 2249.96   573.2 2276.11   589.6 2285.08     619 2307.24
   628.8  2310.9   707.4 2366.36   779.3 2419.49   870.9 2489.57   926.6 2528.19
#Mann= 3 ,-1 , 0
       0     .12       0  454.51    .045       0   468.5     .12       0
Bank Sta=454.51,468.5
XS Rating Curve= 0 ,0
Exp/Cntr=0.3,0.1

Type RM Length L Ch R = 1 ,16914   ,348.2,350,354.1
XS GIS Cut Line= 3
     2143482.184      240019.814     2143150.484      240334.114
     2142827.717      240657.996
#Sta/Elev= 30
       0 2268.54    52.2 2257.66   159.9 2232.27   182.8 2220.29   202.4 2212.74
   215.4 2209.89   277.4 2207.85   378.6 2207.89   385.2 2206.16   394.9 2199.03
   430.8 2198.94   449.5 2195.37   463.5 2195.29   464.5 2195.36   479.8 2201.64
     519 2205.87   535.3  2214.4   564.7 2235.44   587.6 2254.03   597.4 2264.67
   607.2 2281.87     617 2290.32   675.8 2330.93     715 2359.88   724.8 2364.22
   734.6 2372.71   786.8 2410.81   855.4 2457.91   884.8 2473.81   914.2 2485.41
#Mann= 3 ,-1 , 0
       0     .12       0   449.5    .045       0   464.5     .12       0
Bank Sta=449.5,464.5
XS Rating Curve= 0 ,0
Exp/Cntr=0.3,0.1

Type RM Length L Ch R = 1 ,16564   ,350.2,350,347.1
XS GIS Cut Line= 3
     2143330.141       239750.48     2142981.028       240036.99
     2142590.557      240303.157
#Sta/Elev= 30
       0 2226.59     9.8 2224.42    39.3 2224.46    98.2 2218.04   117.8 2221.47
   147.3 2221.26   166.9 2219.57   202.9 2210.86   317.4 2205.04   340.4 2206.72
   356.7 2205.33   366.5  2208.9   382.9  2208.7   392.7  2205.8   405.8 2197.14
   428.7 2195.65   444.1 2190.85   451.6 2190.38   459.1 2190.72   487.5 2192.02
   510.3 2198.94     582 2196.99   591.8 2199.51   637.4 2228.59   709.1 2278.98
   735.2 2304.42     771 2316.79   819.9 2342.78   855.8 2358.52   924.2 2377.34
#Mann= 3 ,-1 , 0
       0     .12       0   444.1    .045       0   459.1     .12       0
#XS Ineff= 2 , 0
          427.24  2201.1  508.77         2206.17
Permanent Ineff=
       F       F
Bank Sta=444.1,459.1
XS Rating Curve= 0 ,0
Exp/Cntr=0.3,0.1