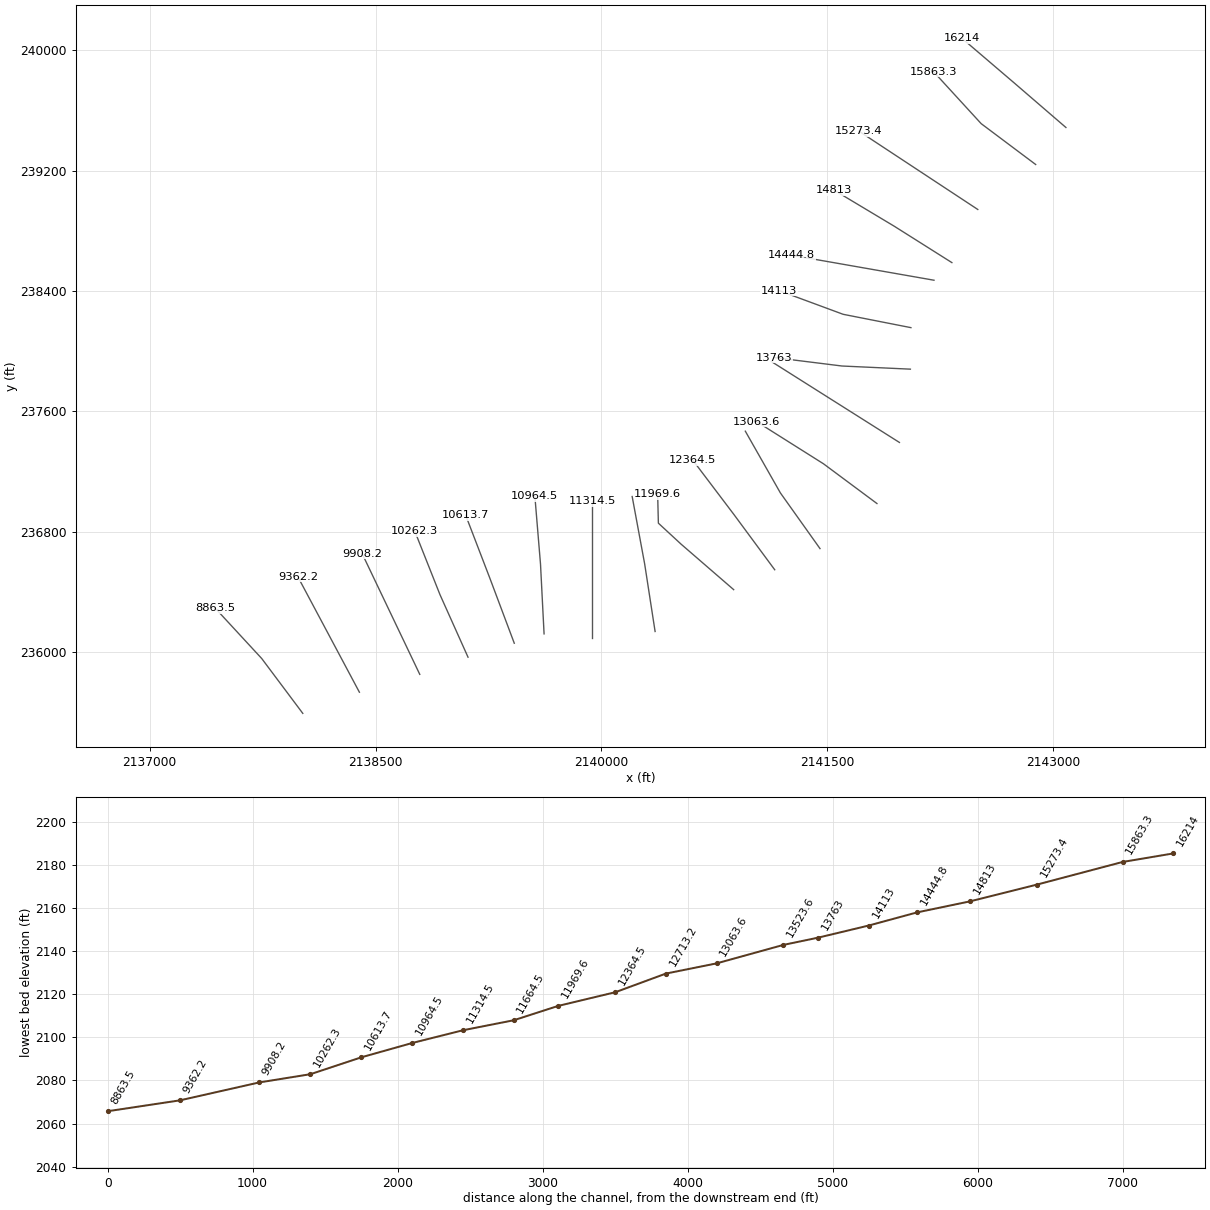
HEC-RAS study LAURELCK3.prj: LAURELCK3

--- LAURELCK3.g01 (geometry) --- (continued)

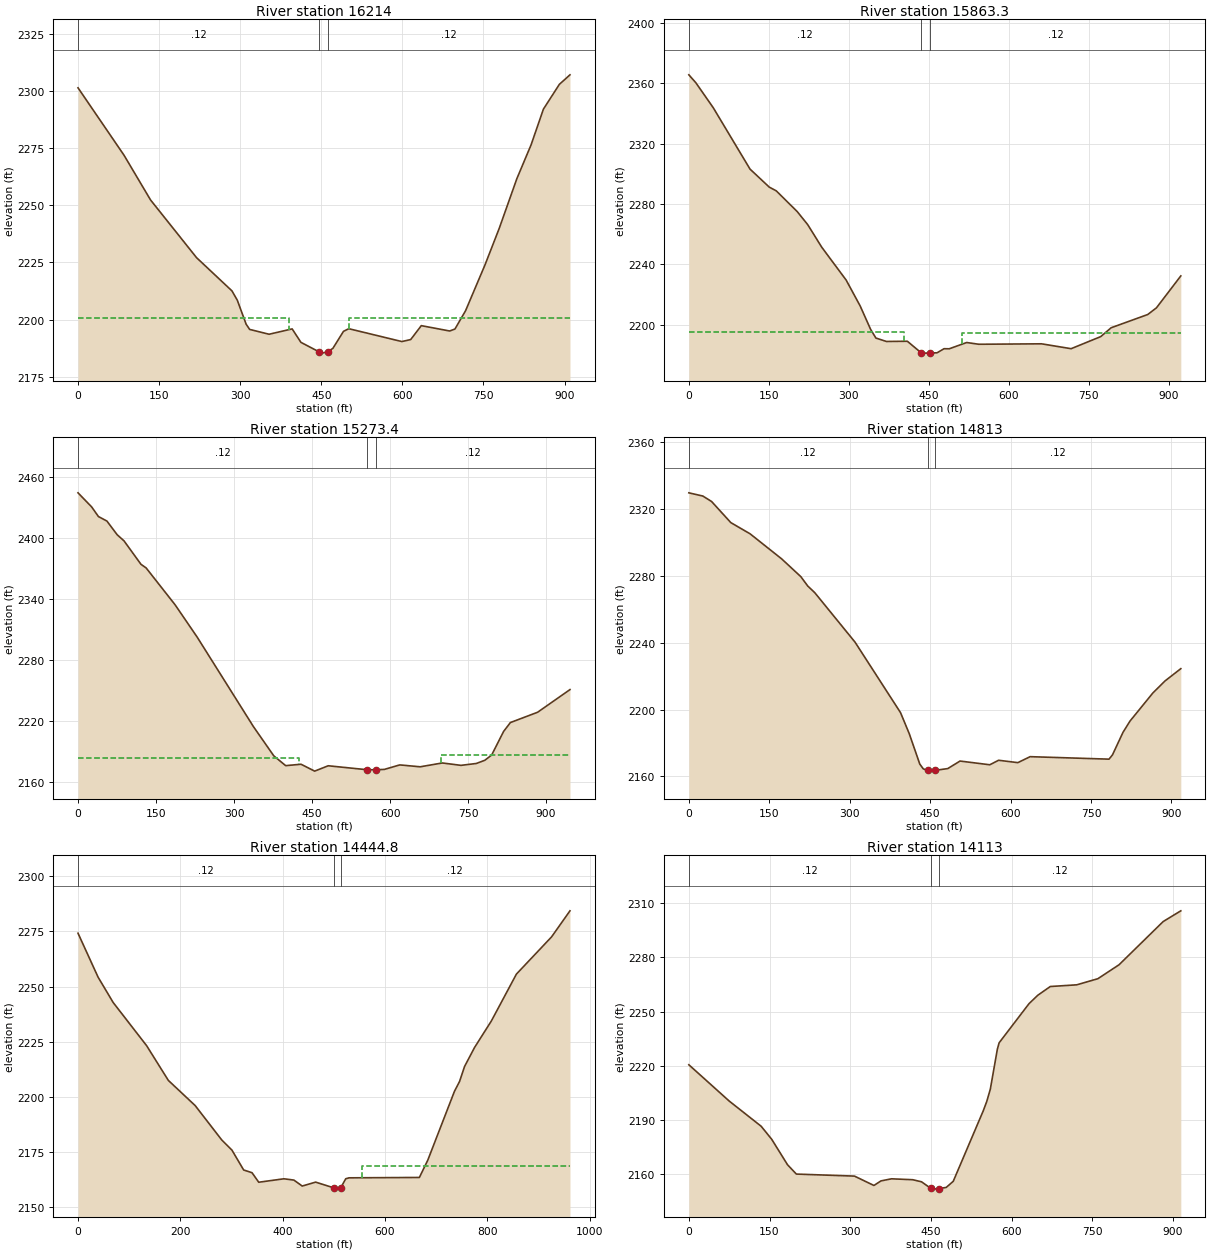
Type RM Length L Ch R = 1 ,16214   ,349,350.6,349.3
XS GIS Cut Line= 3
     2143086.769      239486.827     2142742.147      239783.912
     2142396.246      240079.517
#Sta/Elev= 30
       0  2301.4    85.1 2271.92   134.2 2252.35   219.3 2227.11   284.8 2212.57
   294.6 2208.53     311 2198.01   317.5 2195.73   353.5 2193.62   396.1 2195.96
   412.4 2190.06  446.12  2185.9   451.7 2185.36   461.6 2185.97   471.4 2187.42
     491 2194.87   500.8 2196.05     599 2190.42   615.4  2191.3     635 2197.38
   687.4 2195.04   697.2 2195.89   716.9 2203.92   752.9    2224   779.1  2239.9
   811.8  2261.7     838 2276.42   860.9 2292.09   890.4 2302.92     910 2307.08
#Mann= 3 ,-1 , 0
       0     .12       0  446.12    .045       0   461.6     .12       0
#XS Ineff= 2 , 0
          390.09 2200.57  501.55         2200.81
Permanent Ineff=
       F       F
Bank Sta=446.12,461.6
XS Rating Curve= 0 ,0
Exp/Cntr=0.3,0.1

Type RM Length L Ch R = 1 ,15863.3 ,589.5,590,593.5
XS GIS Cut Line= 3
     2142885.746      239240.808     2142523.866      239512.217
     2142206.438      239858.852
#Sta/Elev= 30
       0 2365.42    13.1 2360.19    45.9 2343.58   114.7 2303.08   150.8 2291.16
   163.9  2288.7   203.2 2274.99   222.9 2266.34   249.1 2251.46     295 2229.66
   321.2 2212.59   340.9 2197.04   350.7 2191.36   370.4  2189.1   409.7 2189.24
     4362181.488   442.5 2181.39   452.4  2181.5   465.4 2181.61   478.5 2184.31
   488.2 2184.26   520.9  2188.4   543.7 2187.25   661.2 2187.55   716.7 2184.32
   772.2  2192.3   791.8 2198.17   860.4 2206.92   876.7 2211.34   922.4 2232.45
#Mann= 3 ,-1 , 0
       0     .12       0     436    .045       0   452.4     .12       0
#XS Ineff= 2 , 0
          402.48 2195.19  511.87         2194.76
Permanent Ineff=
       F       F
Bank Sta=436,452.4
XS Rating Curve= 0 ,0
Exp/Cntr=0.3,0.1

Type RM Length L Ch R = 1 ,15273.4 ,457.4,460.3,460.3
XS GIS Cut Line= 2
     2142501.275      238941.781     2141711.558      239462.426
#Sta/Elev= 30
       0 2444.13    26.2 2430.31    39.3 2420.83    55.6  2416.4    75.3 2402.98
    88.4 2396.99   121.1 2373.93   130.9 2370.44   186.6 2334.26   229.1 2302.49
   337.1 2214.75   376.4 2185.92   399.3 2176.28   428.8 2177.66     455  2170.9
   481.1 2176.16   556.4 2172.24   572.8 2172.24   589.1  2172.6   618.6 2177.01
   657.9 2175.15   700.4 2178.91   736.4 2176.57   765.9 2178.42   782.2 2181.56
   795.3 2186.68   818.2 2209.79   831.3 2218.57   883.7 2228.71   945.9 2250.94
#Mann= 3 ,-1 , 0
       0     .12       0   556.4    .045       0   572.8     .12       0
#XS Ineff= 2 , 0
          425.18 2183.45  698.66         2186.99
Permanent Ineff=
       F       F
Bank Sta=556.4,572.8
XS Rating Curve= 0 ,0
Exp/Cntr=0.3,0.1

Type RM Length L Ch R = 1 ,14813   ,357.8,368.3,375.9
XS GIS Cut Line= 3
     2142329.143      238588.598     2141945.796      238830.716
     2141547.832      239069.383
#Sta/Elev= 30
       0 2329.63    26.1  2327.7    42.4 2324.44    78.3  2311.8   114.2 2305.11
   172.9 2290.16   208.8 2279.49   221.8 2273.86   234.9 2269.86   309.9  2240.3
   394.7 2198.15     411 2185.56   430.6 2167.39   437.1 2164.52  445.022163.589
   450.1 2163.14  458.632163.589   482.8 2164.66   505.7 2169.17   561.2 2166.94
   577.6 2169.64   613.5 2168.22   636.4 2171.79   783.5  2170.3     790 2172.88
   809.6 2186.36   822.7  2193.1   865.2 2209.86     888 2217.11   917.4 2224.44
#Mann= 3 ,-1 , 0
       0     .12       0  445.02    .045       0  458.63     .12       0
Bank Sta=445.02,458.63
XS Rating Curve= 0 ,0
Exp/Cntr=0.3,0.1

Type RM Length L Ch R = 1 ,14444.8 ,333,331.7,327.3
XS GIS Cut Line= 2
     2142210.327      238471.451     2141263.103      238637.707
#Sta/Elev= 30
       0 2274.22    39.2 2254.27    68.7 2242.75   134.1 2223.14   176.6 2207.35
     229 2195.93   281.3 2180.21   300.9 2175.69   323.8 2166.67   340.2 2165.42
   353.3  2161.1   402.4 2162.66     422 2162.08   438.3 2159.37   464.5 2161.15
   499.7 2158.57     507 2157.97   513.6 2158.58   523.4 2162.69   529.9  2163.1
   667.3 2163.27   683.7  2171.1     736 2202.46   745.8 2206.84   755.6 2213.66
   775.2 2222.32     808 2234.34     857 2255.64   925.7 2272.54   961.7 2284.38
#Mann= 3 ,-1 , 0
       0     .12       0   499.7    .045       0   513.6     .12       0
#XS Ineff= 2 , 0
                          554.18         2168.38
Permanent Ineff=
       F       F
Bank Sta=499.7,513.6
XS Rating Curve= 0 ,0
Exp/Cntr=0.3,0.1

Type RM Length L Ch R = 1 ,14113   ,346.3,350,355.2
XS GIS Cut Line= 3
     2142057.008      238156.186     2141606.875      238244.845
     2141179.267      238403.012
#Sta/Elev= 30
       0 2220.62    75.4 2200.48   134.4 2186.66     154 2179.47   183.5 2165.36
   199.9 2160.22     308 2159.09   344.1 2153.92   357.2 2156.45   376.9  2157.6
   416.2  2157.1   432.6 2155.95  450.182152.261   455.5  2151.9   465.3 2152.22
   478.5 2152.83   491.6 2156.23   547.3 2195.12   553.9 2200.35   560.5  2207.1
   573.6 2229.22   576.9 2232.77   632.6 2254.44     649 2259.08     672 2263.86
   721.2  2264.8   760.5 2268.18   799.9  2275.9   881.9 2299.76   914.7 2305.69
#Mann= 3 ,-1 , 0
       0     .12       0  450.18    .045       0   465.3     .12       0
Bank Sta=450.18,465.3
XS Rating Curve= 0 ,0
Exp/Cntr=0.3,0.1

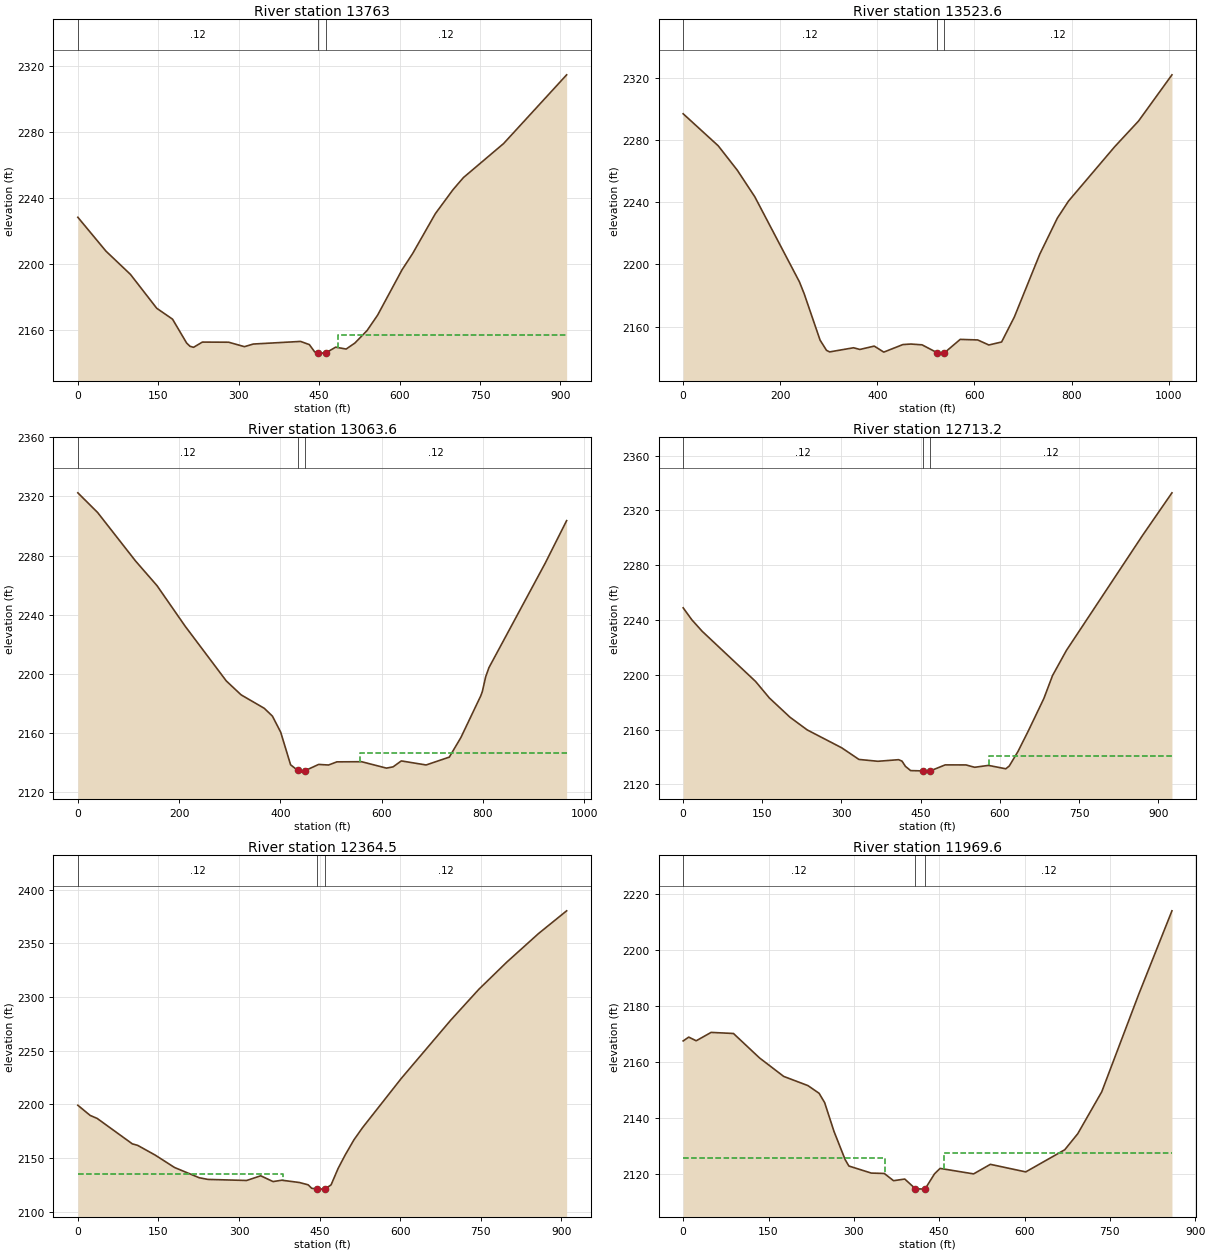
Type RM Length L Ch R = 1 ,13763   ,250.9,239.4,229
XS GIS Cut Line= 3
     2142053.502      237880.238     2141599.329      237901.119
     2141145.867      237957.595
#Sta/Elev= 30
       0 2228.34    52.3 2207.92    98.1 2193.83   147.2 2173.34   176.6 2166.78
   202.8 2152.39   209.3 2150.35   215.9 2149.78   232.2 2152.93   281.3 2152.85
   310.7 2150.16   327.1 2151.75   415.4 2153.33   431.8  2151.4   441.6 2147.03
   447.2 2146.37   451.4 2146.26   462.2 2146.35   480.8 2149.86   500.4 2148.73
   516.7 2152.36   539.5 2159.94   559.1 2169.24   604.8  2196.7   624.4 2206.43
   666.8 2230.55   699.5 2244.94     719 2252.29   794.1  2272.9   911.6 2314.41
#Mann= 3 ,-1 , 0
       0     .12       0   447.2    .045       0   462.2     .12       0
#XS Ineff= 2 , 0
                          486.07         2157.03
Permanent Ineff=
       F       F
Bank Sta=447.2,462.2
XS Rating Curve= 0 ,0
Exp/Cntr=0.3,0.1

Type RM Length L Ch R = 1 ,13523.6 ,461.1,460,459.4
XS GIS Cut Line= 2
      2141980.63      237392.972      2141129.66      237931.118
#Sta/Elev= 30
       0 2296.72    72.2 2276.15   111.5 2260.46   147.6 2243.35   239.4 2188.75
   249.2  2181.1     282 2151.26   295.2 2144.72   301.7 2143.69   350.9 2146.35
     364 2145.26   393.6 2147.42   413.2 2143.55   452.6 2148.41     469 2148.73
     492 2148.24  523.282143.136     528  2142.9   537.9 2143.06   570.7 2151.74
   606.7 2151.37   629.7 2148.13   655.9 2150.06   682.2 2166.16   734.6 2206.54
   770.7 2229.65   793.7 2240.61   888.8 2275.54     938 2292.07  1006.8 2321.76
#Mann= 3 ,-1 , 0
       0     .12       0  523.28    .045       0   537.9     .12       0
Bank Sta=523.28,537.9
XS Rating Curve= 0 ,0
Exp/Cntr=0.3,0.1

Type RM Length L Ch R = 1 ,13063.6 ,357.3,350.4,338.8
XS GIS Cut Line= 3
     2141831.382      236986.903      2141475.83      237251.292
     2141033.885      237530.124
#Sta/Elev= 30
       0 2322.44    39.1 2309.11     114 2276.36   156.4  2259.7   211.8 2232.38
   293.2 2195.32   322.5  2185.9   368.2 2176.82   384.4 2171.51   400.7 2160.68
   420.3 2138.61  434.552134.796   443.1 2134.34   449.6 2134.76   475.7 2138.87
   495.3 2138.47   511.7 2140.61   560.6  2140.7   609.6 2136.38   622.7 2137.21
     639 2141.24     688  2138.5   733.8 2143.81   756.6 2156.98   795.8 2185.09
   799.1 2188.12   805.6 2198.04   812.1 2204.27   923.2 2274.84   965.6 2303.64
#Mann= 3 ,-1 , 0
       0     .12       0  434.55    .045       0   449.6     .12       0
#XS Ineff= 2 , 0
                          557.28         2146.45
Permanent Ineff=
       F       F
Bank Sta=434.55,449.6
XS Rating Curve= 0 ,0
Exp/Cntr=0.3,0.1

Type RM Length L Ch R = 1 ,12713.2 ,347.2,348.6,351.2
XS GIS Cut Line= 3
     2141453.003      236687.319     2141189.983      237057.247
     2140956.855      237467.944
#Sta/Elev= 30
       0 2248.88    16.3  2240.2    35.9 2231.79   137.2  2195.1   163.3 2183.05
   202.5 2168.94   235.1 2159.69   300.4 2146.63   333.1 2138.13     369 2136.78
   408.2 2137.95   414.7 2136.89   421.2 2133.06     431 2129.98   453.9 2129.75
   463.7 2129.59  468.242129.763   496.5 2134.15   535.9 2134.12   552.3 2132.39
   578.5 2133.78   611.3  2131.3   617.9 2133.31   634.3 2143.85     654 2158.95
   683.5 2182.68   699.9  2199.4   726.1 2217.71   870.4 2301.75   926.2  2332.9
#Mann= 3 ,-1 , 0
       0     .12       0   453.9    .045       0  468.24     .12       0
#XS Ineff= 2 , 0
                          578.95         2140.54
Permanent Ineff=
       F       F
Bank Sta=453.9,468.24
XS Rating Curve= 0 ,0
Exp/Cntr=0.3,0.1

Type RM Length L Ch R = 1 ,12364.5 ,389.6,394.9,399.4
XS GIS Cut Line= 3
      2141152.12      236546.689     2140881.924      236912.821
     2140607.513       237275.75
#Sta/Elev= 30
       0 2199.09    22.9 2189.63      36 2186.82   101.5 2163.11   111.3 2161.75
     144 2152.66     180 2141.12   225.9 2131.57   242.2    2130   314.3 2129.01
   340.5 2133.38   363.4 2127.99   379.7 2129.25   412.5 2127.12   428.8 2124.96
   435.4 2121.71   445.2 2121.15   458.3 2120.95  459.95 2121.13   471.4 2124.86
   484.5 2140.17   497.6 2152.69     514 2166.89   530.3 2178.41   602.3  2224.2
     694 2278.26   746.4 2307.07   798.7 2332.52   857.7  2359.1     910 2380.27
#Mann= 3 ,-1 , 0
       0     .12       0   445.2    .045       0  459.95     .12       0
#XS Ineff= 2 , 0
          381.17 2135.08
Permanent Ineff=
       F       F
Bank Sta=445.2,459.95
XS Rating Curve= 0 ,0
Exp/Cntr=0.3,0.1

Type RM Length L Ch R = 1 ,11969.6 ,320.9,305.1,289.7
XS GIS Cut Line= 4
     2140879.462      236414.427      2140530.56      236716.452
     2140379.234      236856.393     2140374.482      237048.004
#Sta/Elev= 30
       0 2167.49     9.8 2168.85    22.9 2167.54    49.1 2170.53    88.4 2170.14
   134.2 2161.42   176.7 2154.82   219.3 2151.54   238.9  2148.8   248.7 2145.46
   265.1  2135.2   284.7 2125.13   291.3 2122.83   330.6 2120.31   353.5 2120.17
   369.8 2117.59   389.5 2118.18  408.03 2114.75   422.2 2114.58   425.5 2114.73
   441.8 2120.04   451.6 2121.98   510.5 2120.02     540 2123.43   602.2 2120.73
   670.8 2128.64   693.6 2134.36   735.8 2149.33   800.8 2184.13   859.2 2213.93
#Mann= 3 ,-1 , 0
       0     .12       0  408.03    .045       0   425.5     .12       0
#XS Ineff= 2 , 0
          355.01 2125.74  459.24         2127.57
Permanent Ineff=
       F       F
Bank Sta=408.03,425.5
XS Rating Curve= 0 ,0
Exp/Cntr=0.3,0.1

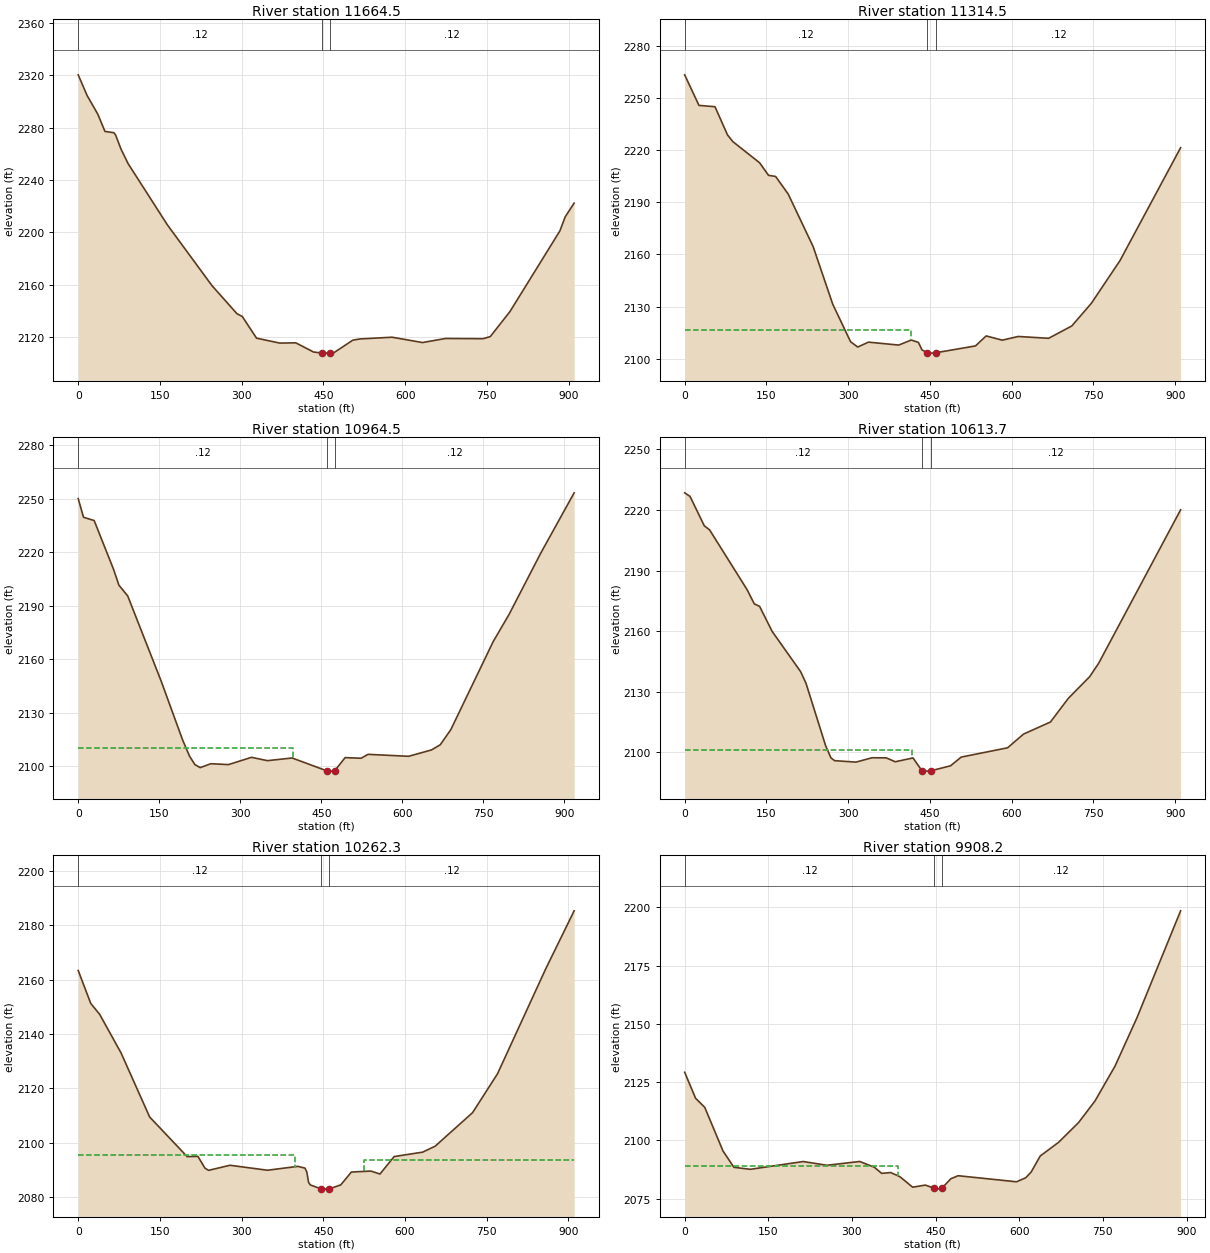
Type RM Length L Ch R = 1 ,11664.5 ,353.4,350,345.9
XS GIS Cut Line= 3
      2140357.48      236136.253     2140288.053      236585.881
     2140205.145      237033.516
#Sta/Elev= 30
       0 2320.17    16.4 2304.32      36 2290.16    49.1 2277.01    65.5 2276.04
    68.7 2274.24    78.6 2263.48    91.6 2252.44   163.6  2205.8   245.5 2159.43
   291.3 2138.02   301.1 2135.91   327.3 2119.36   369.9 2115.61   399.3  2115.8
     432 2108.78   447.5 2108.03   462.5 2107.99   468.1 2107.95   504.1 2117.86
   517.2 2118.77   576.1 2120.08   631.8 2116.02   674.4 2119.12   743.2 2118.95
   756.3 2120.58   792.3 2139.59     884 2201.14   893.8 2211.93   910.2 2222.35
#Mann= 3 ,-1 , 0
       0     .12       0   447.5    .045       0   462.5     .12       0
Bank Sta=447.5,462.5
XS Rating Curve= 0 ,0
Exp/Cntr=0.3,0.1

Type RM Length L Ch R = 1 ,11314.5 ,348.7,350,351.7
XS GIS Cut Line= 3
     2139940.851      236092.142     2139940.851      236547.142
     2139940.851      237002.142
#Sta/Elev= 30
       0 2263.26    26.2 2245.69    55.6 2244.93    78.6 2228.72    88.4 2224.86
   137.5 2212.72   153.8 2205.51   166.9 2204.84   189.9 2194.78   235.7 2164.55
   271.7 2131.41   304.4 2109.87   317.5  2106.8   337.2 2109.62   392.8 2107.94
   415.7 2110.84   428.8  2109.5   435.4  2105.2   445.2 2103.58     455 2103.31
   461.6 2103.57   533.6 2107.45   553.2  2113.2   582.7 2110.76   612.1 2112.88
   667.8 2111.83   710.3 2118.92   746.3 2131.98   798.7 2156.46     910 2221.39
#Mann= 3 ,-1 , 0
       0     .12       0   445.2    .045       0   461.6     .12       0
#XS Ineff= 2 , 0
          414.86 2116.72
Permanent Ineff=
       F       F
Bank Sta=445.2,461.6
XS Rating Curve= 0 ,0
Exp/Cntr=0.3,0.1

Type RM Length L Ch R = 1 ,10964.5 ,343.6,350.8,356.8
XS GIS Cut Line= 3
     2139619.897       236120.35     2139596.186      236584.525
     2139558.656      237036.223
#Sta/Elev= 30
       0    2250     9.8 2239.55    29.5 2237.72    65.5 2210.34    75.3 2201.52
    91.6 2195.52   153.8 2147.61   193.1 2114.97   206.2  2105.7     216 2101.07
   225.8 2099.36   245.5 2101.54   278.2 2101.06   320.8 2105.13   350.2 2103.26
     396 2104.76  460.172097.569     468  2097.4   474.6 2097.55   494.1 2104.97
   523.5  2104.6   536.5  2106.8   611.5  2105.7   653.9 2109.26   670.2 2112.17
   689.8 2120.68     768 2169.85   797.4 2185.08   856.1 2219.42     918 2253.23
#Mann= 3 ,-1 , 0
       0     .12       0  460.17    .045       0   474.6     .12       0
#XS Ineff= 2 , 0
          397.32 2110.41
Permanent Ineff=
       F       F
Bank Sta=460.17,474.6
XS Rating Curve= 0 ,0
Exp/Cntr=0.3,0.1

Type RM Length L Ch R = 1 ,10613.7 ,349.7,351.4,351.6
XS GIS Cut Line= 3
     2139421.893      236058.291     2139262.043      236484.304
     2139099.039      236909.101
#Sta/Elev= 30
       0 2228.44     9.8 2226.69      36 2212.12    45.8 2210.09   114.6  2180.5
   127.7 2173.52   137.5 2172.26   160.4 2159.94   212.8 2139.96   222.6 2134.24
   258.6 2103.37   268.4 2097.32     275 2095.94   314.3 2095.22   343.7 2097.37
   369.9 2097.32   386.3 2095.39     419 2097.29   435.4 2090.93   445.2 2090.76
   451.7 2090.94   487.8 2093.39   507.4  2097.7   592.5  2102.3     622 2109.12
   671.1 2115.05   703.8 2126.71   743.1 2137.48   759.4 2144.02     910 2220.04
#Mann= 3 ,-1 , 0
       0     .12       0   435.4    .045       0   451.7     .12       0
#XS Ineff= 2 , 0
          416.92 2101.08
Permanent Ineff=
       F       F
Bank Sta=435.4,451.7
XS Rating Curve= 0 ,0
Exp/Cntr=0.3,0.1

Type RM Length L Ch R = 1 ,10262.3 ,353.5,354.2,355.5
XS GIS Cut Line= 3
     2139114.657       235965.35     2138928.277      236381.291
     2138760.602      236804.119
#Sta/Elev= 30
       0 2163.36      23 2151.25    39.4 2147.23    78.7 2133.01   131.2 2109.45
     200 2094.89   219.7 2094.97   232.8 2090.63   239.4 2089.83   278.7  2091.7
   347.6 2089.87   403.3  2091.3   416.4 2090.65   419.7 2089.23     423 2085.39
   426.3 2084.45     446 2083.01   455.8 2082.92  460.582082.994     482 2084.47
   501.6 2089.21   537.6 2089.56     554 2088.47   580.1  2094.9   632.5 2096.53
   655.4 2098.72   724.1 2111.06   769.9 2125.36   858.3 2163.92   910.6 2185.31
#Mann= 3 ,-1 , 0
       0     .12       0     446    .045       0  460.58     .12       0
#XS Ineff= 2 , 0
          398.35 2095.61  524.25         2093.58
Permanent Ineff=
       F       F
Bank Sta=446,460.58
XS Rating Curve= 0 ,0
Exp/Cntr=0.3,0.1

Type RM Length L Ch R = 1 ,9908.2  ,542.4,546,546.8
XS GIS Cut Line= 2
     2138794.049      235851.246     2138411.221      236654.089
#Sta/Elev= 30
       0 2129.21    19.6 2118.04      36 2114.17    68.7 2095.46    88.3 2088.44
   117.7 2087.58   212.6 2090.92   255.1 2089.31   313.9 2090.94   340.1 2088.48
   353.2 2085.85   369.5 2086.19   385.9 2084.43   408.8 2079.91   431.6 2080.81
     448 2079.42   451.3 2079.08     461  2079.4   477.4 2083.55   490.5 2084.83
   595.1 2082.23   611.5 2083.93   621.3 2086.38   637.6 2093.28   670.4 2099.13
   706.3 2107.61   735.8 2116.88   771.7 2131.82     811 2152.54   889.4 2198.47
#Mann= 3 ,-1 , 0
       0     .12       0     448    .045       0     461     .12       0
#XS Ineff= 2 , 0
          381.84 2089.09
Permanent Ineff=
       F       F
Bank Sta=448,461
XS Rating Curve= 0 ,0
Exp/Cntr=0.3,0.1

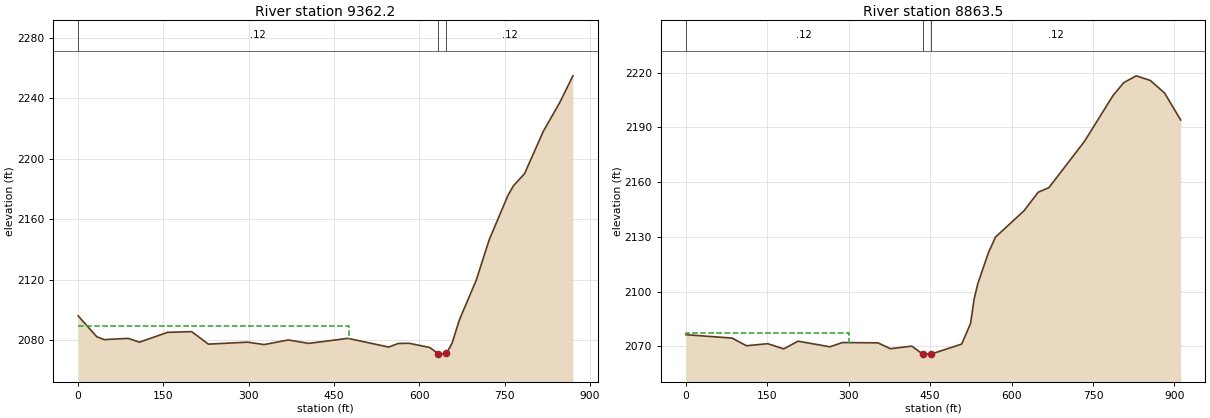
Type RM Length L Ch R = 1 ,9362.2  ,494.9,498.7,503
XS GIS Cut Line= 2
     2138392.993      235732.596     2137983.914      236500.438
#Sta/Elev= 30
       0 2096.12    32.7  2082.3    45.8 2080.39    88.3  2081.2   107.9 2078.69
     157 2085.18   199.5 2085.67     229 2077.39   297.6  2078.7   327.1  2077.1
   369.6 2080.15   405.6  2077.9   474.3 2081.23   546.2 2075.44   562.6 2077.82
   582.2 2077.95   618.2 2075.17   632.7 2071.18   644.3 2070.78   647.7  2071.3
   657.4 2077.91   670.5 2093.56   699.9 2119.61   722.8 2146.49   755.5 2175.63
   765.4 2182.19     785 2190.23   817.7 2218.09   847.1 2237.49     870 2254.98
#Mann= 3 ,-1 , 0
       0     .12       0   632.7    .045       0   647.7     .12       0
#XS Ineff= 2 , 0
          475.75  2089.7
Permanent Ineff=
       F       F
Bank Sta=632.7,647.7
XS Rating Curve= 0 ,0
Exp/Cntr=0.3,0.1

Type RM Length L Ch R = 1 ,8863.5  ,354.9,350.2,344.4
XS GIS Cut Line= 3
     2138016.906      235591.866     2137744.018      235956.598
     2137434.761      236291.634
#Sta/Elev= 30
       0 2076.39    85.2 2074.53   111.4 2070.32   150.8 2071.46   180.2  2068.6
   206.5 2072.83   265.4 2069.75   288.4 2072.09   353.9  2071.9   376.9  2068.7
   416.2 2070.12   435.9 2065.84   439.1 2065.73   452.2 2065.81     508 2071.23
   524.4 2082.59     531 2095.95   537.5 2104.08   557.2 2121.26   570.3 2129.89
   622.8  2144.3     649  2154.5   668.7 2156.99   734.3 2182.39   786.8 2207.47
   806.5 2214.53   829.5 2218.31   855.7 2215.75     882 2208.84   911.5  2194.1
#Mann= 3 ,-1 , 0
       0     .12       0   435.9    .045       0   452.2     .12       0
#XS Ineff= 2 , 0
          300.31  2077.3
Permanent Ineff=
       F       F
Bank Sta=435.9,452.2
XS Rating Curve= 0 ,0
Exp/Cntr=0.3,0.1