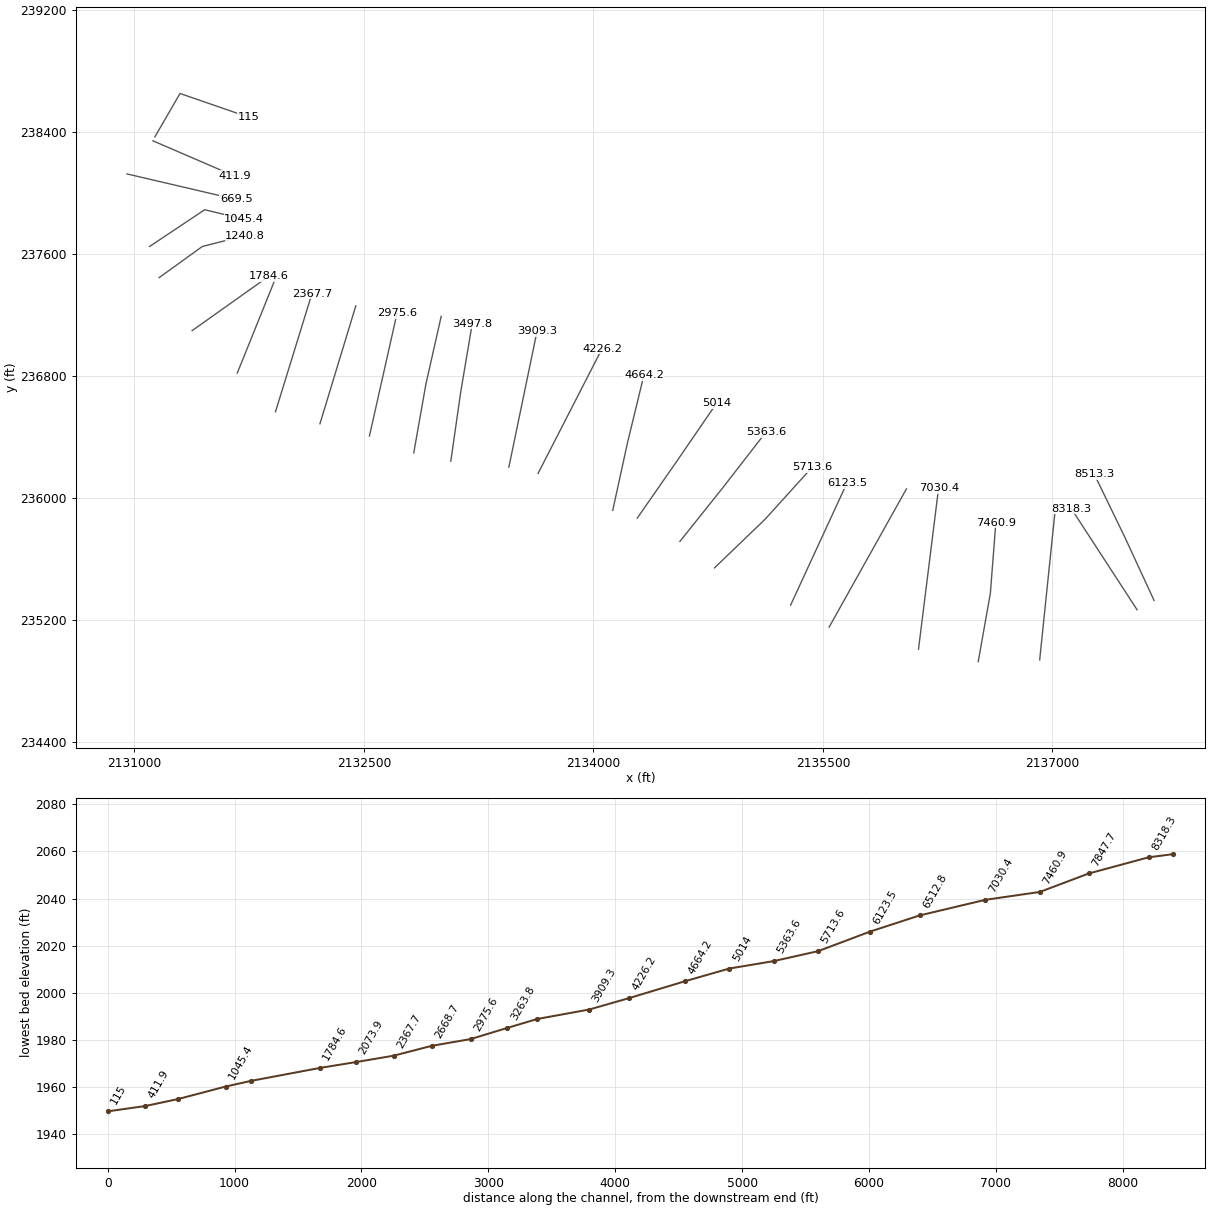
HEC-RAS study LAURELCK3.prj: LAURELCK3

--- LAURELCK3.g01 (geometry) --- (continued)

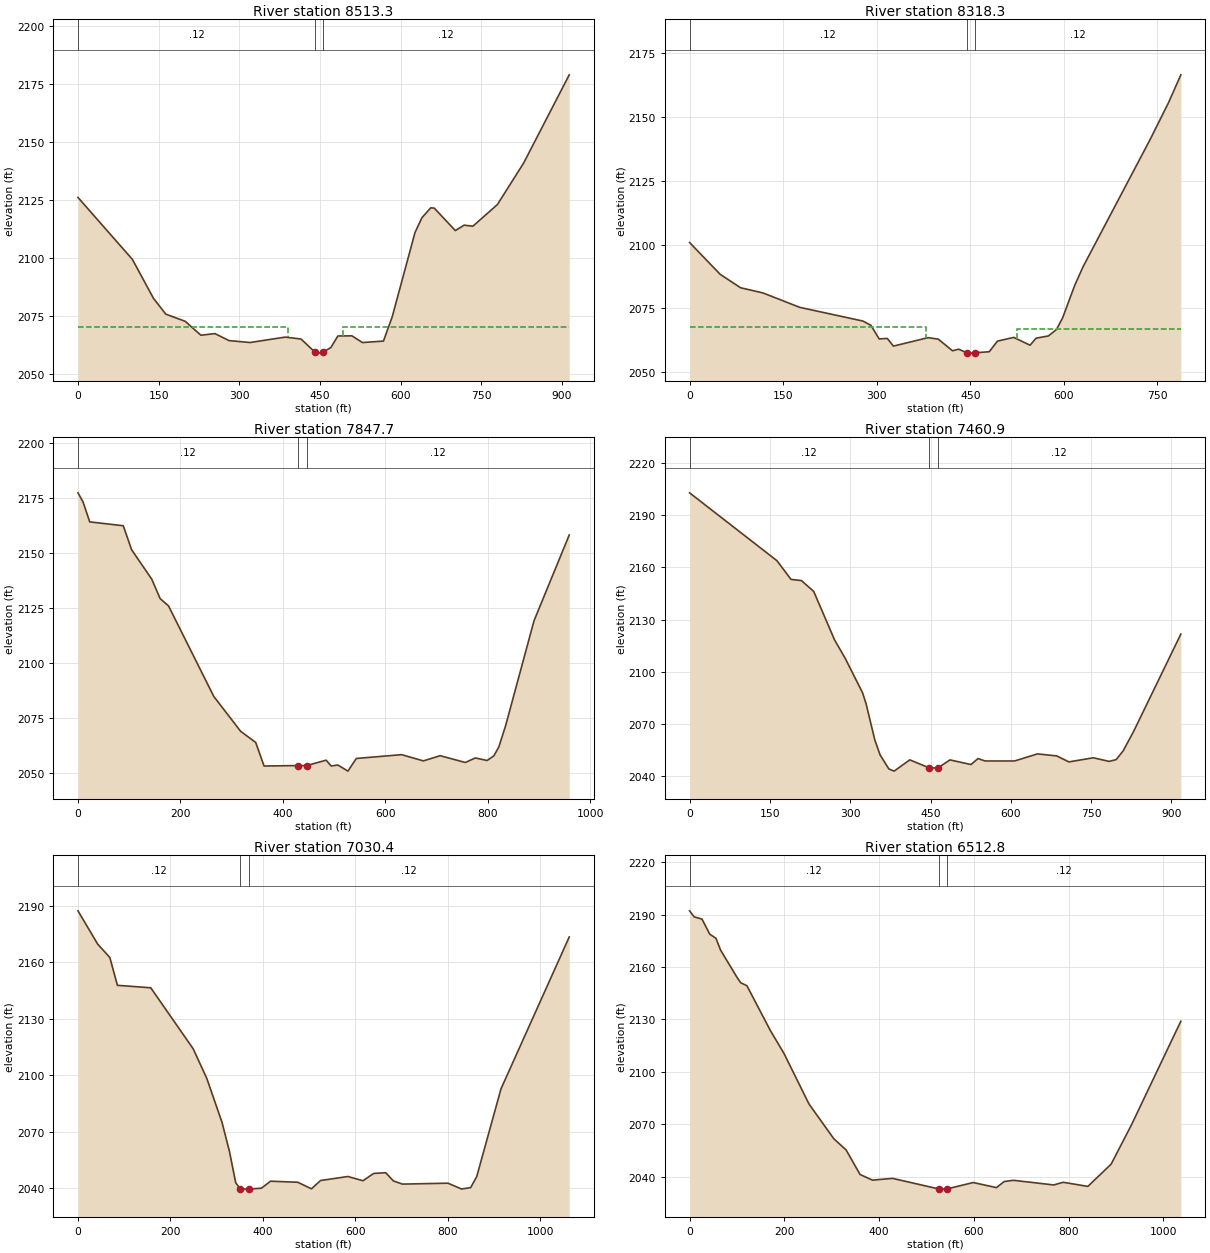
Type RM Length L Ch R = 1 ,8513.3  ,191.3,195.1,197.4
XS GIS Cut Line= 3
     2137663.842       235330.13     2137473.522      235742.493
     2137273.383      236156.384
#Sta/Elev= 30
       0 2125.96   101.3 2099.24   140.5 2082.47   163.4 2075.67   199.3  2072.6
   228.7 2066.58   254.8 2067.28     281 2064.27   320.2 2063.44   385.6 2065.78
     415 2064.94   441.1 2059.25   447.6 2058.87  455.852059.277   470.5 2061.29
   483.5 2066.26   509.6 2066.32   529.2 2063.43   568.3 2064.06   584.6 2074.53
     627 2110.85     640 2117.27   656.3 2121.48   662.8 2121.36     702 2111.67
   718.3 2114.01   734.6 2113.55   780.2 2122.87   829.1 2140.78   913.9 2178.79
#Mann= 3 ,-1 , 0
       0     .12       0   441.1    .045       0  455.85     .12       0
#XS Ineff= 2 , 0
          391.12 2070.03  493.29         2070.27
Permanent Ineff=
       F       F
Bank Sta=441.1,455.85
XS Rating Curve= 0 ,0
Exp/Cntr=0.3,0.1

Type RM Length L Ch R = 1 ,8318.3  ,486.7,470.6,452.5
XS GIS Cut Line= 2
      2137552.96      235268.828     2137124.194      235929.478
#Sta/Elev= 30
       0 2100.77      49 2088.35    81.7 2083.09   117.6 2081.06   176.5 2075.43
   277.8 2070.07   290.8 2068.38   303.9 2063.08     317 2063.26   326.8 2060.27
   382.4 2063.57   398.7 2062.99   421.6 2058.43   431.4 2059.07   444.4 2057.66
   447.7 2057.52   457.5 2057.66   480.4 2058.06   493.5 2062.21   519.6 2063.67
   545.8 2060.62   555.6 2063.37   575.2 2064.24   588.2 2066.75     598 2071.28
   617.6 2084.11   630.7 2091.24   738.6 2141.19     768 2155.54   787.6 2166.36
#Mann= 3 ,-1 , 0
       0     .12       0   444.4    .045       0   457.5     .12       0
#XS Ineff= 2 , 0
          379.77 2067.67  524.25         2066.96
Permanent Ineff=
       F       F
Bank Sta=444.4,457.5
XS Rating Curve= 0 ,0
Exp/Cntr=0.3,0.1

Type RM Length L Ch R = 1 ,7847.7  ,387.6,386.8,386.6
XS GIS Cut Line= 2
     2136916.373       234940.69     2137014.815      235894.477
#Sta/Elev= 30
       0 2177.35     9.8 2173.26    22.9 2164.13    88.4 2162.36   104.7 2151.43
     144 2138.04   160.4 2129.19   176.7 2125.88   265.1 2084.65   317.4 2068.81
   346.9 2063.71   363.2 2052.98  430.392053.197  446.552053.188   484.3 2055.65
   494.2    2053   507.2 2053.43   526.9 2050.66   543.2 2056.42   631.6 2058.16
   674.1 2055.32   706.9 2057.68     756  2054.6   775.6 2056.66   798.5  2055.5
   811.6  2057.6   821.4 2061.67   834.5 2071.23   890.1 2119.12   958.8 2158.16
#Mann= 3 ,-1 , 0
       0     .12       0  430.39    .045       0  446.55     .12       0
Bank Sta=430.39,446.55
XS Rating Curve= 0 ,0
Exp/Cntr=0.3,0.1

Type RM Length L Ch R = 1 ,7460.9  ,428.8,430.5,428.8
XS GIS Cut Line= 3
     2136514.766      234929.392      2136594.01      235376.197
     2136629.826       235838.59
#Sta/Elev= 30
       0  2202.9   163.2 2163.84   189.4  2153.1   208.9 2152.41   231.8  2146.2
     271 2118.16   290.6 2107.73   323.2 2087.79   329.7  2081.5     346 2060.72
   355.8 2052.13   372.2 2044.06     382 2042.79   411.3 2049.28   447.2 2044.71
   463.6  2044.6   486.4 2049.25   525.6 2046.58   538.7 2050.03   551.8 2048.64
   607.3 2048.64   649.7  2052.7   685.7 2051.55   708.5  2048.1   754.2 2050.47
   783.6 2048.39   796.7 2049.42   809.8 2054.42   829.4 2065.64   917.6 2121.64
#Mann= 3 ,-1 , 0
       0     .12       0   447.2    .045       0   463.6     .12       0
Bank Sta=447.2,463.6
XS Rating Curve= 0 ,0
Exp/Cntr=0.3,0.1

Type RM Length L Ch R = 1 ,7030.4  ,525.1,517.6,509
XS GIS Cut Line= 2
     2136124.468      235010.693     2136255.723      236065.109
#Sta/Elev= 30
       0 2187.24    42.6 2169.57    68.9 2162.47    85.3 2147.68   157.4 2146.37
   249.2 2113.97   278.8 2098.13   311.6 2074.88     328 2059.07   341.1  2042.9
   350.9 2039.55     364 2039.43   370.6 2039.47   396.8 2039.94   416.5 2043.64
   475.5 2043.08     505  2039.6   524.7    2044   583.8 2046.14   616.5 2043.88
   639.5 2047.76   665.7 2048.15   682.1  2043.8   701.8  2042.1   800.2 2042.58
   829.7  2039.5   849.4 2040.24   862.5 2046.09     915 2092.69  1062.6 2173.35
#Mann= 3 ,-1 , 0
       0     .12       0   350.9    .045       0   370.6     .12       0
Bank Sta=350.9,370.6
XS Rating Curve= 0 ,0
Exp/Cntr=0.3,0.1

Type RM Length L Ch R = 1 ,6512.8  ,385.3,389.3,391.1
XS GIS Cut Line= 2
     2135540.383      235155.074     2136045.715      236060.733
#Sta/Elev= 30
       0 2192.13     9.8 2188.65    26.2 2187.41    42.5 2178.79    55.6 2176.41
    65.4 2169.66   101.4 2153.48     108 2150.94     121 2149.26   170.1  2123.8
   199.6 2110.31   251.9 2081.61   304.3 2061.68   330.4 2055.24   359.9 2041.17
     386 2037.94   428.6 2038.94   526.7 2032.86   539.8 2032.79   543.1 2032.87
   598.7 2036.57   647.8 2033.65   664.1 2037.13   683.8 2037.84   768.8 2035.18
   788.5 2036.72   840.8 2034.35   889.9 2047.09   932.4 2069.34  1037.1 2128.94
#Mann= 3 ,-1 , 0
       0     .12       0   526.7    .045       0   543.1     .12       0
Bank Sta=526.7,543.1
XS Rating Curve= 0 ,0
Exp/Cntr=0.3,0.1

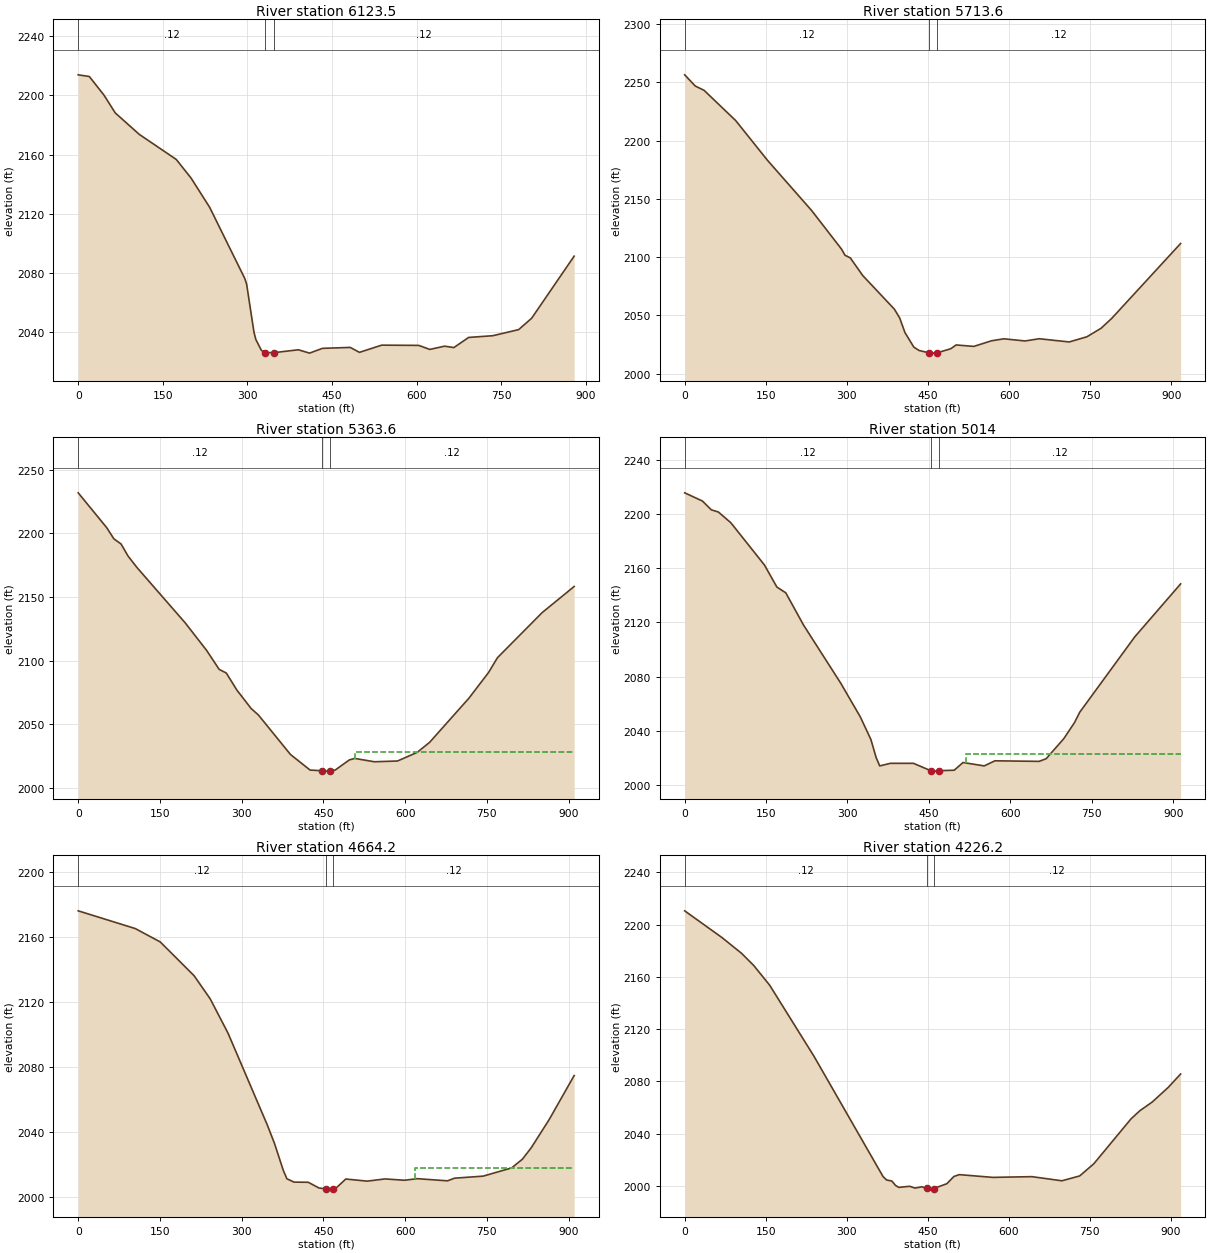
Type RM Length L Ch R = 1 ,6123.5  ,418.2,409.9,403
XS GIS Cut Line= 2
     2135288.811      235299.454     2135656.325      236097.922
#Sta/Elev= 30
       0 2213.92    19.7 2212.79    45.9  2200.1    65.6 2188.22   108.2 2173.71
   173.8 2156.77   200.1 2144.14   232.9  2124.5   295.2 2076.38   298.5 2072.54
   311.6 2039.92   314.9  2035.1   324.7 2027.78   331.3 2026.28   347.7 2026.29
   390.3 2028.21     410 2025.94   432.9 2029.17   482.1  2029.8   498.5 2026.47
   537.9 2031.33   603.5 2031.17   623.2 2028.45   649.4 2030.64   665.8  2029.7
     692 2036.54   734.7  2037.7   780.6 2041.82   803.6 2049.47     879 2091.44
#Mann= 3 ,-1 , 0
       0     .12       0   331.3    .045       0   347.7     .12       0
Bank Sta=331.3,347.7
XS Rating Curve= 0 ,0
Exp/Cntr=0.3,0.1

Type RM Length L Ch R = 1 ,5713.6  ,346.8,350,351.2
XS GIS Cut Line= 3
     2134791.231      235543.118     2135122.233      235862.016
     2135428.906      236201.705
#Sta/Elev= 30
       0 2256.53    19.6  2246.9    35.9 2243.23    94.5  2217.2   153.2 2183.14
   234.7 2140.12   290.1 2106.91   296.6 2101.62   306.4 2099.35   329.2  2084.3
   387.9 2055.35   397.7 2047.77   407.5 2035.21   423.8 2022.81   433.6 2019.88
   452.1 2017.86   456.4 2017.62   467.1 2017.88   492.3 2021.42   502.1 2024.64
   534.8 2023.39   567.5 2028.21   590.4 2029.92   629.6 2028.06   655.8 2029.97
   711.3 2027.21     744 2031.66   770.2 2038.97   789.8 2047.41   917.3 2111.74
#Mann= 3 ,-1 , 0
       0     .12       0   452.1    .045       0   467.1     .12       0
Bank Sta=452.1,467.1
XS Rating Curve= 0 ,0
Exp/Cntr=0.3,0.1

Type RM Length L Ch R = 1 ,5363.6  ,347.9,349.5,350.7
XS GIS Cut Line= 3
     2134565.248      235716.441     2134848.754      236072.313
     2135127.181      236432.229
#Sta/Elev= 30
       0 2231.81    52.4 2204.41    65.5 2195.68    78.6 2191.68    91.6 2182.09
     108  2173.1   196.4 2129.72   235.7 2108.08   258.6 2093.27   271.7 2090.38
   291.3  2076.9   317.5 2062.44   330.6 2057.46   389.5 2026.44   425.5 2014.21
   447.5 2013.69     455 2013.38   462.5 2013.71   471.4 2014.18   497.6  2022.2
   507.4 2023.35   543.4 2020.73   585.9 2021.32     622  2028.1   644.9 2036.02
   716.9 2070.62   752.9 2090.76   769.3 2102.42   851.1 2137.72     910 2158.31
#Mann= 3 ,-1 , 0
       0     .12       0   447.5    .045       0   462.5     .12       0
#XS Ineff= 2 , 0
                          508.77         2028.29
Permanent Ineff=
       F       F
Bank Sta=447.5,462.5
XS Rating Curve= 0 ,0
Exp/Cntr=0.3,0.1

Type RM Length L Ch R = 1 ,5014    ,341,349.8,357.8
XS GIS Cut Line= 3
     2134286.856      235869.545     2134545.666        236242.8
     2134805.275      236622.077
#Sta/Elev= 30
       0 2215.51    32.7 2209.46      49    2203    62.1 2201.36      85 2193.48
     147 2162.27   169.9 2146.01   186.3 2141.76   218.9 2118.05   287.6 2075.06
   323.5 2050.33   343.1  2033.6   352.9 2020.13   359.4 2014.06     379 2015.99
   421.5 2015.99   454.2 2010.43   457.5 2010.23  468.772010.568   496.6  2010.9
   512.9 2016.58     552 2014.09   571.6 2017.84     653 2017.43   666.1 2019.38
   698.7 2034.26   718.2 2045.99     728 2053.71   829.1 2109.17   913.8 2148.33
#Mann= 3 ,-1 , 0
       0     .12       0   454.2    .045       0  468.77     .12       0
#XS Ineff= 2 , 0
                          519.09          2022.8
Permanent Ineff=
       F       F
Bank Sta=454.2,468.77
XS Rating Curve= 0 ,0
Exp/Cntr=0.3,0.1

Type RM Length L Ch R = 1 ,4664.2  ,443.7,438,432.3
XS GIS Cut Line= 3
     2134126.213      235919.712     2134223.099       236364.25
     2134330.212      236806.613
#Sta/Elev= 30
       0 2176.14   104.7 2165.22   150.6 2156.98   212.8 2136.14   242.2 2121.97
     275 2100.78     347 2044.32     360 2033.13   376.4 2016.33     383 2011.19
   396.1 2009.14   422.2 2009.03   441.9 2005.51     455 2004.94   461.5 2004.82
   468.12005.068   474.6 2005.91     491 2011.04   530.3 2009.74     563  2011.1
     599 2010.28     622 2011.26   677.6 2009.93   690.7 2011.56   743.1 2012.82
   795.5 2017.89   815.2 2023.27   831.5 2030.36   864.3 2047.65   910.1 2074.74
#Mann= 3 ,-1 , 0
       0     .12       0     455    .045       0   468.1     .12       0
#XS Ineff= 2 , 0
                          617.13         2017.94
Permanent Ineff=
       F       F
Bank Sta=455,468.1
XS Rating Curve= 0 ,0
Exp/Cntr=0.3,0.1

Type RM Length L Ch R = 1 ,4226.2  ,310.7,316.9,323.1
XS GIS Cut Line= 2
     2133638.136      236161.445     2134056.538      236979.153
#Sta/Elev= 30
       0 2210.48    68.9  2190.1     105 2178.11   127.9 2168.69   157.5 2153.56
   239.5 2099.26   367.4 2007.28     374 2004.68   383.8 2003.84   390.4 2000.52
   396.9 1998.99   416.6 1999.87   426.5 1998.48   439.6 1999.47   447.9 1998.18
     456 1997.68  461.02  1998.1   485.5 2001.82   498.6 2007.34   508.5 2008.77
   570.8 2006.66     643 2007.22   698.7 2004.06   731.6 2007.78   757.8  2017.1
   826.7 2051.43   843.1 2057.66     866 2064.32   895.6 2075.48   918.5  2085.7
#Mann= 3 ,-1 , 0
       0     .12       0   447.9    .045       0  461.02     .12       0
Bank Sta=447.9,461.02
XS Rating Curve= 0 ,0
Exp/Cntr=0.3,0.1

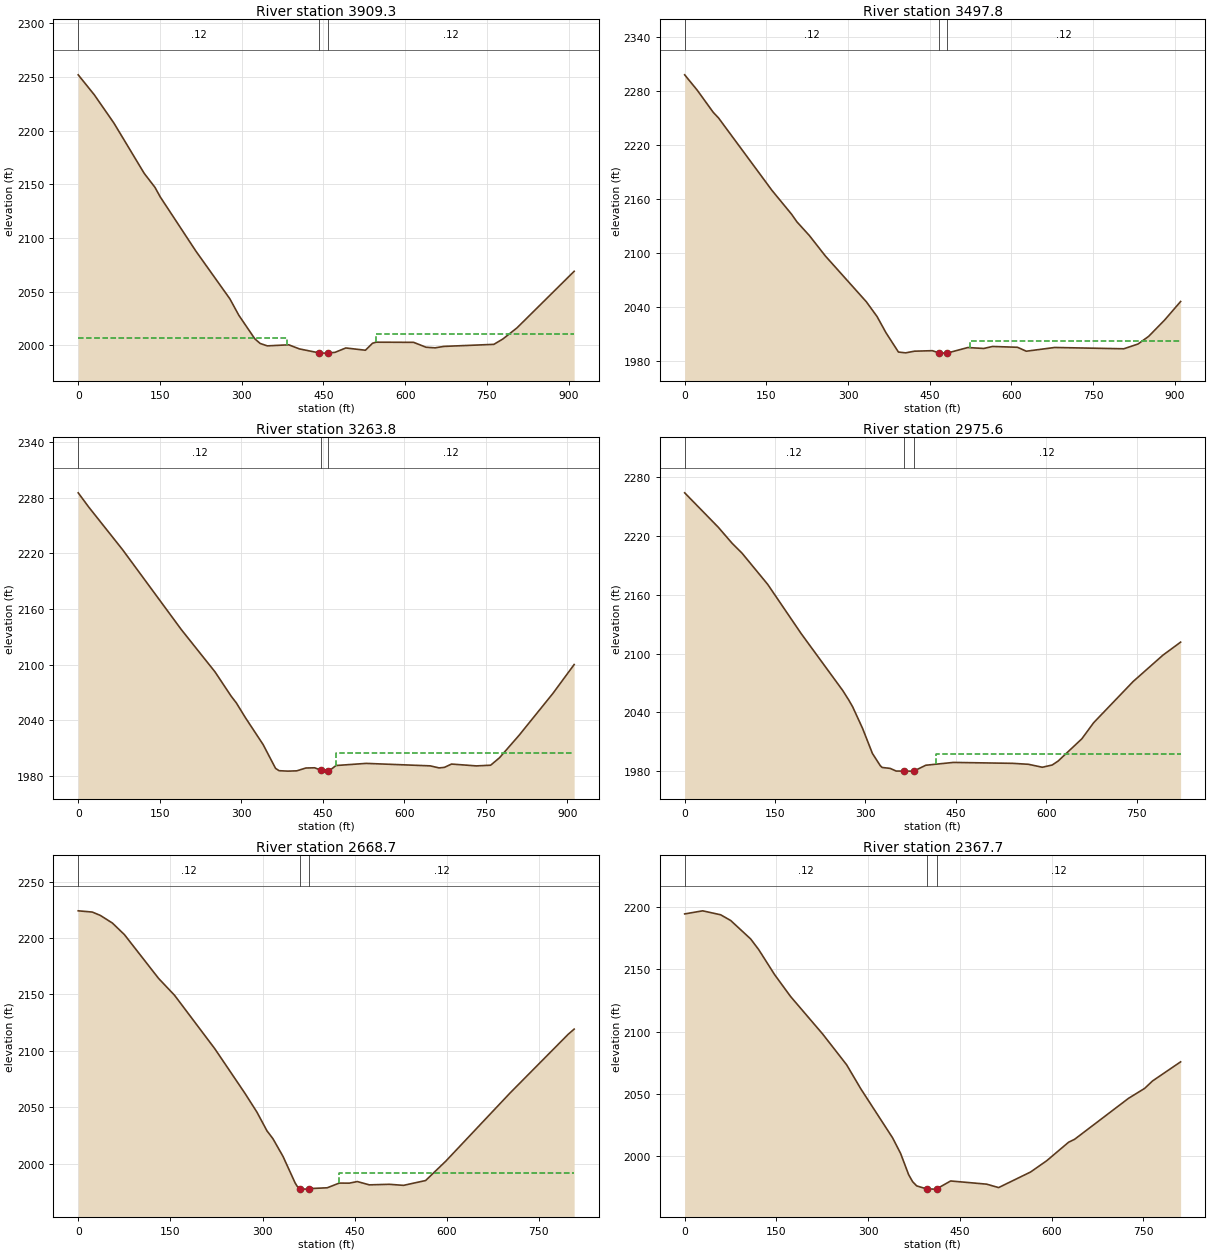
Type RM Length L Ch R = 1 ,3909.3  ,410.5,411.5,412.1
XS GIS Cut Line= 3
     2133447.451      236202.965     2133539.637      236648.528
     2133631.822      237094.092
#Sta/Elev= 30
       0  2252.1    29.5  2233.5    65.5 2207.16   121.1  2160.3   140.8 2147.28
   150.6 2138.28     216 2087.79   278.2 2043.44   294.6 2028.17   324.1  2006.1
   333.9 2001.78     347 1999.55   386.3 2000.55   405.9 1996.71   441.9 1993.04
   448.4 1992.79   458.3 1992.87   471.4 1993.54     491  1997.6     527 1995.48
   540.1 2002.02   546.6 2002.98   615.4 2002.84   638.3 1998.27   654.7 1997.72
     671 1999.05   762.7 2000.97   779.1 2005.92   805.2 2016.36     910 2069.03
#Mann= 3 ,-1 , 0
       0     .12       0   441.9    .045       0   458.3     .12       0
#XS Ineff= 2 , 0
          382.87 2006.76  545.92          2010.9
Permanent Ineff=
       F       F
Bank Sta=441.9,458.3
XS Rating Curve= 0 ,0
Exp/Cntr=0.3,0.1

Type RM Length L Ch R = 1 ,3497.8  ,234.2,234,232.8
XS GIS Cut Line= 3
     2133068.061      236242.117     2133132.383       236692.36
      2133207.96      237142.109
#Sta/Elev= 30
       0 2298.37    22.9 2281.41    52.4 2256.68    62.2 2250.38   160.3 2169.84
   196.3 2143.31   206.1 2134.85     229 2119.57   258.5 2096.76   333.8 2045.79
   353.4 2029.41   369.7 2011.48   392.6 1989.96   405.7 1989.04   422.1  1990.9
   454.8 1991.46   467.7 1988.87   471.1 1988.74   482.7 1988.89     520 1994.96
   549.3 1993.92   565.6 1996.15   611.2 1995.26   627.5 1990.87   679.6 1995.02
   806.6 1993.58   832.7 1998.88   852.2 2007.39   881.6  2025.6   910.9 2046.18
#Mann= 3 ,-1 , 0
       0     .12       0   467.7    .045       0   482.7     .12       0
#XS Ineff= 2 , 0
                          523.22         2002.03
Permanent Ineff=
       F       F
Bank Sta=467.7,482.7
XS Rating Curve= 0 ,0
Exp/Cntr=0.3,0.1

Type RM Length L Ch R = 1 ,3263.8  ,288.9,288.2,287.8
XS GIS Cut Line= 3
     2132825.955      236296.244     2132905.371      236747.142
     2133005.195      237190.541
#Sta/Elev= 30
       0 2285.24    19.6  2269.7    81.8 2223.76   189.7 2137.66   251.8 2091.93
   281.2 2065.97     291 2058.47   307.4 2042.79   340.1 2013.67     363 1987.97
   369.5 1985.42   385.9 1984.96   402.2 1985.28   418.6 1988.31     435 1988.56
  447.05 1985.77  459.44 1985.57   464.4 1986.54   474.2    1991   529.8 1993.31
   647.5 1990.64   663.8 1988.44   673.6 1989.01   686.7 1992.58   732.5  1990.6
   758.7 1991.34     775  1999.4     811 2023.62   873.1 2068.72   912.3 2099.96
#Mann= 3 ,-1 , 0
       0     .12       0  447.05    .045       0  459.44     .12       0
#XS Ineff= 2 , 0
                          474.72         2004.39
Permanent Ineff=
       F       F
Bank Sta=447.05,459.44
XS Rating Curve= 0 ,0
Exp/Cntr=0.3,0.1

Type RM Length L Ch R = 1 ,2975.6  ,308.5,306.9,305.1
XS GIS Cut Line= 2
     2132536.303      236406.921     2132716.424      237209.872
#Sta/Elev= 30
       0 2263.66    55.7 2228.65    78.7 2212.29    95.1 2202.25   137.7 2170.49
   193.4  2120.2   262.3 2062.31   272.1 2052.81   278.7 2045.75   295.1 2023.87
   311.5 1998.26   324.6 1985.73   327.8 1983.94     341 1983.02   350.8 1980.33
   363.9 1980.24     377 1980.23   380.3 1980.28     400 1986.22   445.9  1989.1
   544.2 1988.16   570.5 1987.18   593.4 1984.18   609.8 1986.46   619.6 1990.47
     659 2013.14   678.6 2029.55   744.2 2071.54   793.4 2098.26   822.9  2111.6
#Mann= 3 ,-1 , 0
       0     .12       0   363.9    .045       0   380.3     .12       0
#XS Ineff= 2 , 0
                          416.92         1997.89
Permanent Ineff=
       F       F
Bank Sta=363.9,380.3
XS Rating Curve= 0 ,0
Exp/Cntr=0.3,0.1

Type RM Length L Ch R = 1 ,2668.7  ,300.8,300.9,300.6
XS GIS Cut Line= 2
     2132212.952      236487.216     2132447.327      237259.785
#Sta/Elev= 30
       0 2224.12    22.9 2223.03      36 2220.05    55.6 2213.31    75.2 2203.04
   130.7 2164.28   156.9 2149.19   222.3 2101.88   271.3  2062.4   290.9 2045.67
   307.2 2029.09     317 2022.05   333.4 2006.34     353 1982.96   356.3 1979.96
   361.51977.835   369.4 1977.35   375.9  1977.8   405.3 1978.54   424.9  1982.7
   441.3 1982.65   454.3 1984.07   473.9 1981.13   506.6 1981.63   529.5 1980.69
   565.5 1984.97   598.2 2002.06   702.7 2062.44   797.5 2114.61   807.3 2119.23
#Mann= 3 ,-1 , 0
       0     .12       0   361.5    .045       0   375.9     .12       0
#XS Ineff= 2 , 0
                          425.18         1991.55
Permanent Ineff=
       F       F
Bank Sta=361.5,375.9
XS Rating Curve= 0 ,0
Exp/Cntr=0.3,0.1

Type RM Length L Ch R = 1 ,2367.7  ,295.2,293.9,291.5
XS GIS Cut Line= 2
     2131922.154      236565.341     2132160.869      237340.081
#Sta/Elev= 30
       0 2194.68    29.4 2197.17    58.8 2193.98    75.2 2189.39   107.9 2174.52
     121 2165.97   147.1 2145.75   173.2 2128.16   225.6 2097.98   264.8 2073.21
   287.7 2054.07     340 2014.33     353 2001.85   366.1  1984.8   372.6 1979.16
   379.2 1975.78   395.5 1973.29   408.6 1973.15   411.9 1973.36   434.8 1979.72
   493.6 1977.15   513.2 1974.39   565.5 1986.95   591.7 1995.97   627.6 2010.91
   637.4 2013.26   725.7  2046.3   751.8 2054.21   764.9 2060.26   810.7 2075.61
#Mann= 3 ,-1 , 0
       0     .12       0   395.5    .045       0   411.9     .12       0
Bank Sta=395.5,411.9
XS Rating Curve= 0 ,0
Exp/Cntr=0.3,0.1

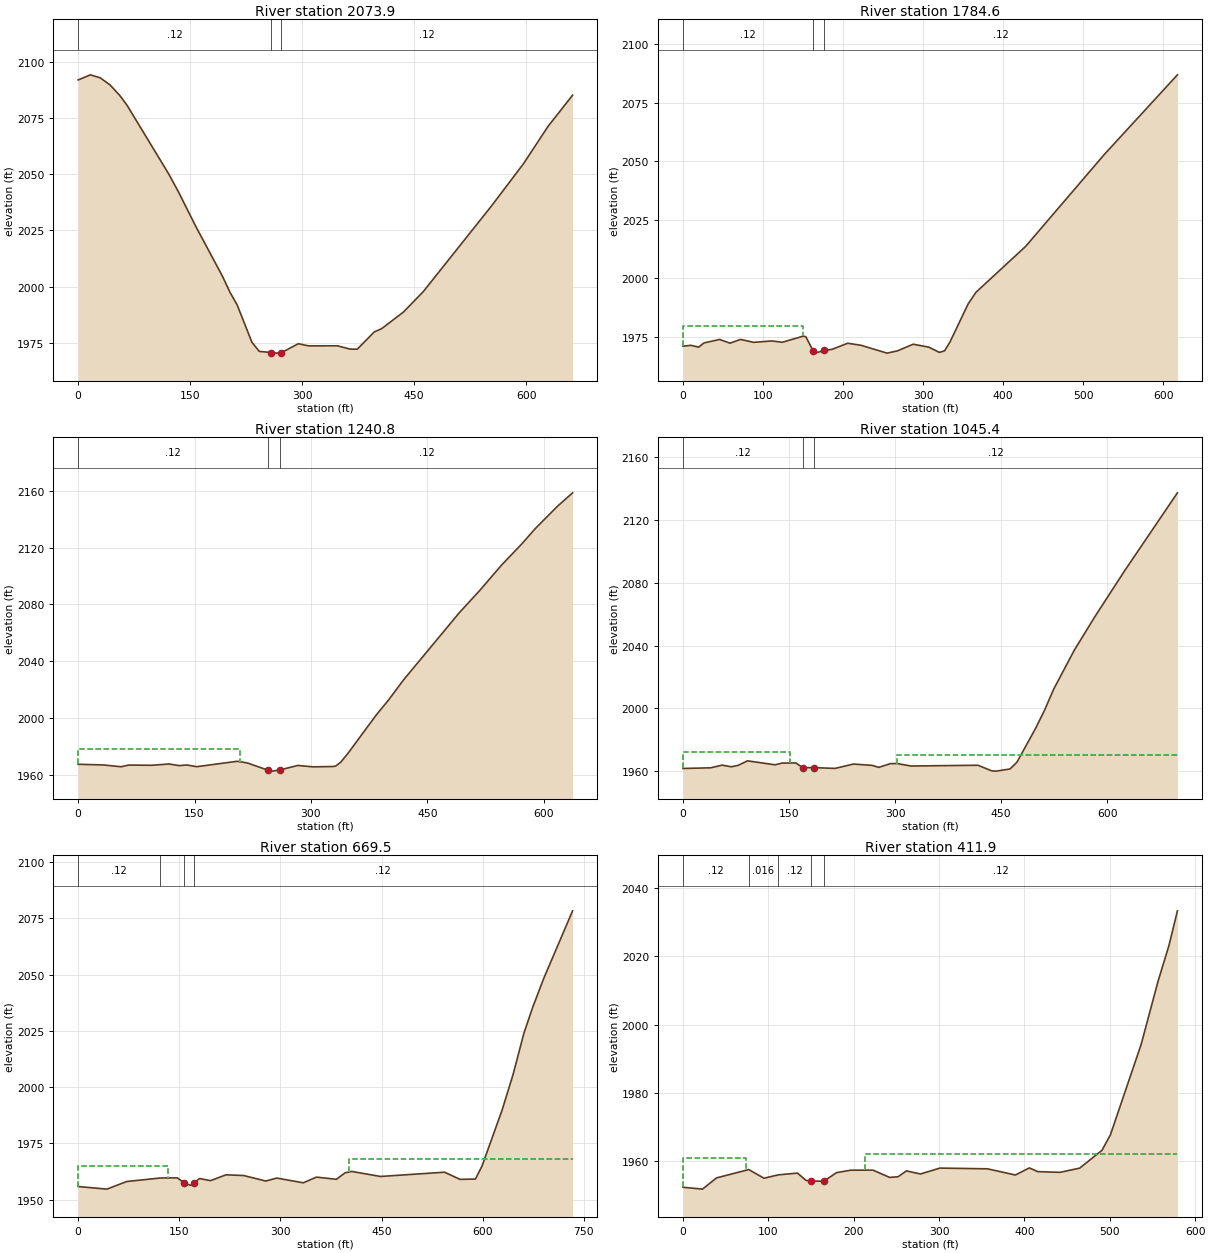
Type RM Length L Ch R = 1 ,2073.9  ,302.1,289.2,276.3
XS GIS Cut Line= 2
     2131672.588      236819.247     2131919.983      237433.397
#Sta/Elev= 30
       0 2091.85    16.4 2094.14    29.5 2092.82    42.6  2089.7    55.7    2085
    65.6 2080.56   121.3 2050.08   134.4 2042.09   157.3 2026.95   193.4 2004.54
   203.2  1997.6     213 1991.84   232.7 1975.31   242.6 1971.23   258.9 1970.74
   265.5 1970.47     272 1970.66     295 1974.66   308.1 1973.71   347.4 1973.72
   363.8 1972.27   373.7  1972.2   396.6  1979.9   406.4 1981.33   435.9 1988.81
   462.2 1997.82   553.9 2036.03   596.6 2054.76   629.3 2071.27   662.1 2085.09
#Mann= 3 ,-1 , 0
       0     .12       0   258.9    .045       0     272     .12       0
Bank Sta=258.9,272
XS Rating Curve= 0 ,0
Exp/Cntr=0.3,0.1

Type RM Length L Ch R = 1 ,1784.6  ,542.2,543.8,543.9
XS GIS Cut Line= 2
     2131377.449      237097.025     2131880.921      237455.098
#Sta/Elev= 30
       0 1970.88     9.8 1971.27    19.6  1970.5    26.2 1972.28    45.8 1973.78
    58.8 1972.19    71.9 1973.78    88.3 1972.54   111.1 1973.14   124.2 1972.58
   150.4  1975.2   153.6  1974.9  162.391969.029   166.7 1968.12   176.5 1969.08
   186.3 1969.55   205.9 1972.16   222.3 1971.29     255 1967.93     268  1968.9
   287.7 1971.74   307.3 1970.47   320.4 1968.24   326.9 1968.92   333.4 1972.54
   356.3 1988.94   366.1 1993.95   428.2 2013.57   526.3 2052.79   617.8 2086.89
#Mann= 3 ,-1 , 0
       0     .12       0  162.39    .045       0   176.5     .12       0
#XS Ineff= 2 , 0
          149.54 1979.63
Permanent Ineff=
       F       F
Bank Sta=162.39,176.5
XS Rating Curve= 0 ,0
Exp/Cntr=0.3,0.1

Type RM Length L Ch R = 1 ,1240.8  ,196.1,195.4,194.4
XS GIS Cut Line= 3
     2131161.824       237444.16     2131443.942      237648.154
      2131723.89      237719.768
#Sta/Elev= 30
       0 1967.25    32.5 1966.76    55.3  1965.5    65.1 1966.68    94.4 1966.53
   117.1 1967.43   130.2 1966.29   139.9 1966.75   152.9 1965.54     205 1969.35
     218 1968.18     244  1963.2   250.5 1962.41   260.3  1963.3   283.1 1966.42
   302.6 1965.42   328.6 1965.67   331.9 1966.01   338.4 1968.73   348.1 1975.24
   383.9 2001.81   400.1 2012.65   419.6 2026.92     491 2073.97     517 2089.44
   546.2 2107.99   572.2 2122.86   588.4 2132.98   617.6 2149.06   637.1 2158.54
#Mann= 3 ,-1 , 0
       0     .12       0     244    .045       0   260.3     .12       0
#XS Ineff= 2 , 0
          208.77 1978.29
Permanent Ineff=
       F       F
Bank Sta=244,260.3
XS Rating Curve= 0 ,0
Exp/Cntr=0.3,0.1

Type RM Length L Ch R = 1 ,1045.4  ,393.9,375.9,356.9
XS GIS Cut Line= 3
     2131099.671       237648.24     2131459.914      237889.126
      2131718.16      237826.192
#Sta/Elev= 30
       0 1961.74    39.1 1962.16    55.4 1963.88    68.4 1962.82    78.2 1963.75
    91.2 1966.61   130.3 1964.08   140.1 1965.17   159.7 1965.24   169.4  1962.3
   185.7 1962.28     215 1961.78   241.1 1964.56   267.2 1963.72     277 1962.46
   293.2 1964.82     303 1964.86   322.6 1963.31   417.1  1963.8   436.6 1960.23
   443.1 1960.05   462.5 1961.43   472.3 1965.75   498.2 1986.96   511.2 1998.75
   524.1 2012.19   553.3 2037.09   582.5 2058.53   624.6 2087.81   699.2 2137.46
#Mann= 3 ,-1 , 0
       0     .12       0   169.4    .045       0   185.7     .12       0
#XS Ineff= 2 , 0
           151.7 1971.96  302.68         1970.61
Permanent Ineff=
       F       F
Bank Sta=169.4,185.7
XS Rating Curve= 0 ,0
Exp/Cntr=0.3,0.1

Type RM Length L Ch R = 1 ,669.5   ,260.9,257.7,253.5
XS GIS Cut Line= 2
     2130952.101      238123.501     2131666.077        237956.4
#Sta/Elev= 30
       0 1955.88    42.6 1954.72      72  1958.1  121.551959.653   147.3 1959.73
   157.1 1957.48     167 1956.39  171.781957.467     180 1959.43   196.4 1958.49
   219.3 1961.08   245.5 1960.76   278.2 1958.32   294.6 1959.63   333.9 1957.53
   353.5 1960.05     383 1959.08   396.1    1962   405.9 1962.57   448.5 1960.34
   543.4 1962.24   566.3 1959.06   589.2 1959.19     599    1965   628.5  1989.6
   644.9 2005.49   661.2 2024.08   674.4  2035.7   690.7 2048.46   733.3 2078.34
#Mann= 4 ,-1 , 0
       0     .12       0  121.55    .016       0   157.1    .045       0
  171.78     .12       0
#XS Ineff= 2 , 0
          133.75 1964.83  402.06         1968.14
Permanent Ineff=
       F       F
Bank Sta=157.1,171.78
XS Rating Curve= 0 ,0
Exp/Cntr=0.3,0.1

Type RM Length L Ch R = 1 ,411.9   ,263.5,296.9,329.9
XS GIS Cut Line= 2
     2131121.372      238340.515     2131653.056       238110.48
#Sta/Elev= 30
       0 1952.31    22.9 1951.76    39.3 1955.05   77.081957.493    94.9 1954.96
  111.591955.939   134.2 1956.46     144 1954.34     150 1954.13     165 1954.09
     180  1956.6   196.4 1957.31   222.6 1957.33   242.2 1955.19     252 1955.39
   261.8 1957.11   278.2  1956.2   301.1 1957.93   356.8 1957.71   389.5  1955.9
   405.8 1957.98   415.7 1956.89   441.8 1956.68   464.8 1957.92   490.9 1963.14
   500.8 1967.68   536.8 1994.18   556.4 2012.52   569.5 2023.29   579.3 2033.35
#Mann= 5 ,-1 , 0
       0     .12       0   77.08    .016       0  111.59     .12       0
     150    .045       0     165     .12       0
#XS Ineff= 2 , 0
            74.3 1960.95     213         1961.96
Permanent Ineff=
       F       F
Bank Sta=150,165
XS Rating Curve= 0 ,0
Exp/Cntr=0.3,0.1

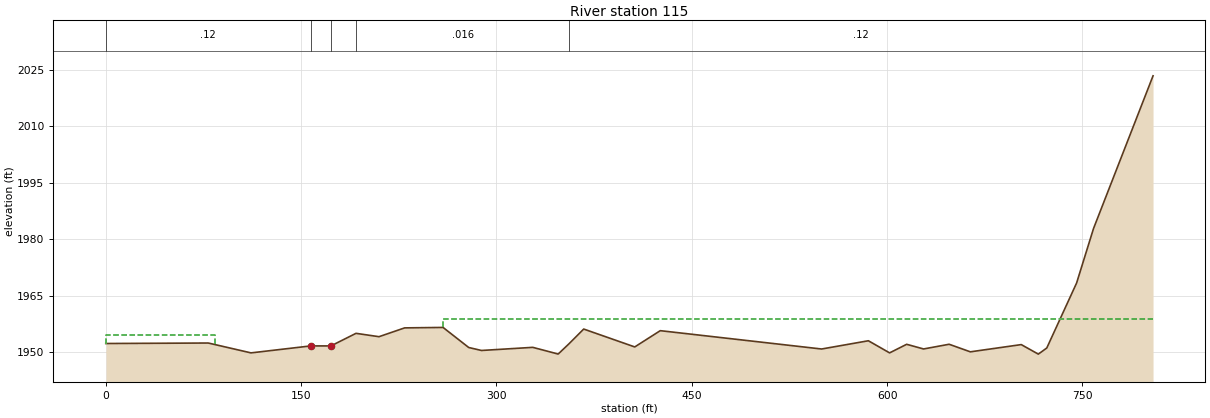
Type RM Length L Ch R = 1 ,115     ,112.5,115,117.3
XS GIS Cut Line= 3
     2131134.393      238366.556     2131298.445      238650.437
     2131748.542      238494.594
#Sta/Elev= 30
       0 1952.31    78.7 1952.44   111.5 1949.82   157.4 1951.67  172.921951.672
  192.161955.012   209.8 1954.12   229.5 1956.46     259 1956.58   278.7 1951.25
   288.5 1950.46   327.9 1951.29   347.4 1949.51  355.761952.257     367 1956.15
   406.2  1951.4   425.8 1955.72   549.7 1950.85   585.6 1953.04   601.9 1949.82
     615  1952.1     628 1950.86   647.6 1952.11   663.9  1950.1     703 1952.02
   716.1 1949.49   722.6 1951.12   745.5 1968.38   758.5 1982.86   804.2 2023.41
#Mann= 5 ,-1 , 0
       0     .12       0   157.4    .045       0  172.92     .12       0
  192.16    .016       0  355.76     .12       0
#XS Ineff= 2 , 0
           83.59 1954.44  259.03         1958.85
Permanent Ineff=
       F       F
Bank Sta=157.4,172.92
XS Rating Curve= 0 ,0
Exp/Cntr=0.3,0.1

Chan Stop Cuts=-1
Use User Specified Reach Order=0
Composite Channel Slope=5